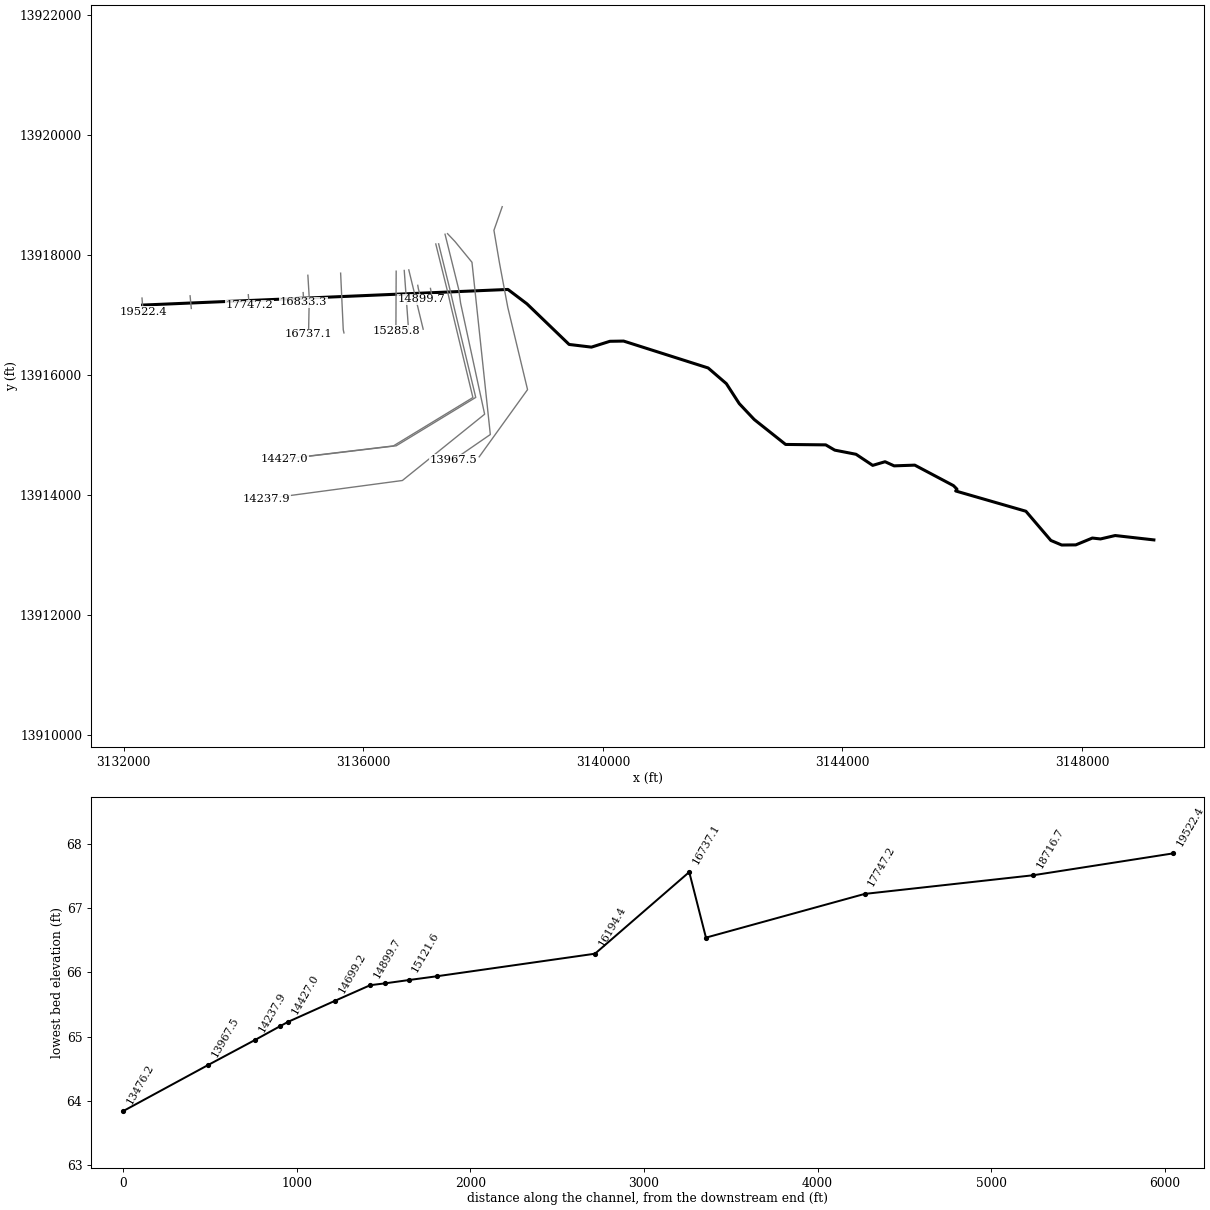
--- P130-05-00.PRJ (project) ---

Proj Title=P130-05-00
Current Plan=p02
Default Exp/Contr=.3,.1
English Units
Geom File=g01
Flow File=f01
Flow File=f02
Plan File=p01
Plan File=p02
Y Axis Title=Elevation
X Axis Title(PF)=Main Channel Distance
X Axis Title(XS)=Station
BEGIN DESCRIPTION:
Greens Bayou Watershed
Reinhardt Bayou
HCFCD Unit P130-05-00
Flood Hazard Model
10, 2, 1, 0.2% Event
Filename P130-05-00.prj
Prepared by:  Watershed Concepts  Date:
Reviewed by:                      Date:
STATUS FINAL
END DESCRIPTION:
DSS Export Rating Curves= 0
DSS Export Rating Curve Sorted= 0
DSS Export Volume Flow Curves= 0
DXF OffsetX= 0
DXF OffsetY= 0
DXF ScaleX= 1
DXF ScaleY= 10

--- P130-05-00.p02 (plan) ---

Plan Title=Floodway
Version=Version 3.0.1  Mar 2001
Short Identifier=Floodway0607
Geom File=g01
Flow File=f02
Subcritical Flow
K Sum by GR= 0
Std Step Tol= 0.01
Critical Tol= 0.01
Num of Std Step Trials= 20
Max Error Tol= 0.3
Flow Tol Ratio= 0.001
Split Flow NTrial= 30
Split Flow Tol= 0.02
Split Flow Ratio= 0.02
Log Output Level= 0
Friction Slope Method= 1
Unsteady Friction Slope Method= 2
Parabolic Critical Depth
Global Vel Dist= 0 , 0 , 0
Global Log Level= 0
CheckData=True
Encroach Param=-1 ,0,0, 2
Encroach River=P130-05-00
Encroach Reach=Reach - 1
Encroach Node=19522.4
       1  4931.5  5068.1
Encroach Node=18716.7
       1  4925.3  5069.1
Encroach Node=17747.2
       1    4929  5070.6
Encroach Node=16833.3
       1  4934.9  5064.7
Encroach Node=16737.1
       1  4934.9  5064.7
Encroach Node=16194.4
       1    4957    5027
Encroach Node=15285.8
       1  4977.1  5024.6
Encroach Node=15121.6
       1  4969.8  5028.9
Encroach Node=14988.1
       1  4935.7  5055.7
Encroach Node=14952.6
       1  4935.7  5055.7
Encroach Node=14899.7
       1  4935.7  5055.7
Encroach Node=14699.2
       1  4943.2  5053.1
Encroach Node=14427.0
       1    4900    5660
Encroach Node=14403.2
       1    4900    5660
Encroach Node=14379.4
       1    4900    5660
Encroach Node=14237.9
       1  4956.6    5620
Encroach Node=13967.5
       1    4937    5650
Encroach Node=13476.2
       1    4820    5700
Encroach Node=12593.5
       1    4690    5250
Encroach Node=11942.4
       1    4510    5212
Encroach Node=11352.3
       1    4660    5264
Encroach Node=10788.7
       1    4800    5420
Encroach Node=10777.7
       1    4800    5420
Encroach Node=10766.7
       1    4800    5420
Encroach Node=10213.3
       1    4950    5215
Encroach Node=9642.0
       1    4970    5227
Encroach Node=8940.4
       1    4976 5030.75
Encroach Node=8406.6
       1  4969.2  5069.5
Encroach Node=7750.2
       1  4969.2  5027.2
Encroach Node=7397.4
       1  4945.7 5045.11
Encroach Node=7134.3
       1 4964.21 5045.11
Encroach Node=7123.8
       1 4964.21 5045.11
Encroach Node=7113.3
       1 4964.21 5045.11
Encroach Node=7086.8
       1  4963.5  5056.2
Encroach Node=6876.8
       1  4963.5  5056.2
Encroach Node=6666.8
       1  4963.5  5056.2
Encroach Node=6030.6
       1  4977.9  5036.8
Encroach Node=5496.7
       1  4951.6  5030.3
Encroach Node=4993.5
       1  4969.6  5026.7
Encroach Node=4872.0
       1  4969.6  5026.7
Encroach Node=4853.0
       1  4969.6  5026.7
Encroach Node=4834.0
       1  4969.6  5026.7
Encroach Node=4454.4
       1  4915.2  5038.5
Encroach Node=3909.8
       1  4956.4  5079.7
Encroach Node=3294.5
       1  4958.6  5084.8
Encroach Node=2288.3
       1  4919.1  5044.8
Encroach Node=1694.6
       1  4903.3  5067.2
Encroach Node=978.3
       1  4929.5    5048
Encroach Reach=P130-05-00_0010
Encroach Node=19522.4
       1  4931.5  5068.1
Encroach Node=18716.7
       1  4925.3  5069.1
Encroach Node=17747.2
       1    4929  5070.6
Encroach Node=16833.3
       1  4934.9  5064.7
Encroach Node=16737.1
       1  4934.9  5064.7
Encroach Node=16194.4
       1    4957    5027
Encroach Node=15285.8
       1  4977.1  5024.6
Encroach Node=15121.6
       1  4969.8  5028.9
Encroach Node=14988.1
       1  4935.7  5055.7
Encroach Node=14952.6
       1  4935.7  5055.7
Encroach Node=14899.7
       1  4935.7  5055.7
Encroach Node=14699.2
       1  4943.2  5053.1
Encroach Node=14427.0
       1    4900    5660
Encroach Node=14403.2
       1    4900    5660
Encroach Node=14379.4
       1    4900    5660
Encroach Node=14237.9
       1  4956.6    5620
Encroach Node=13967.5
       1    4937    5650
Encroach Node=13476.2
       1    4820    5700
Encroach Node=12593.5
       1    4690    5250
Encroach Node=11942.4
       1    4510    5212
Encroach Node=11352.3
       1    4660    5264
Encroach Node=10788.7
       1    4800    5420
Encroach Node=10777.7
       1    4800    5420
Encroach Node=10766.7
       1    4800    5420
Encroach Node=10213.3
       1    4950    5215
Encroach Node=9642.0
       1    4970    5227
Encroach Node=8940.4
       1    4976 5030.75
Encroach Node=8406.6
       1  4969.2  5069.5
Encroach Node=7750.2
       1  4969.2  5027.2
Encroach Node=7397.4
       1  4945.7 5045.11
Encroach Node=7134.3
       1 4964.21 5045.11
Encroach Node=7123.8
       1 4964.21 5045.11
Encroach Node=7113.3
       1 4964.21 5045.11
Encroach Node=7086.8
       1  4963.5  5056.2
Encroach Node=6876.8
       1  4963.5  5056.2
Encroach Node=6666.8
       1  4963.5  5056.2
Encroach Node=6030.6
       1  4977.9  5036.8
Encroach Node=5496.7
       1  4951.6  5030.3
Encroach Node=4993.5
       1  4969.6  5026.7
Encroach Node=4872.0
       1  4969.6  5026.7
Encroach Node=4853.0
       1  4969.6  5026.7
Encroach Node=4834.0
       1  4969.6  5026.7
Encroach Node=4454.4
       1  4915.2  5038.5
Encroach Node=3909.8
       1  4956.4  5079.7
Encroach Node=3294.5
       1  4958.6  5084.8
Encroach Node=2288.3
       1  4919.1  5044.8
Encroach Node=1694.6
       1  4903.3  5067.2
Encroach Node=978.3
       1  4929.5    5048
Computation Interval=1HOUR
Output Interval=1HOUR
Run HTab= 0
Run UNet= 0
Run PostProcess= 0
UNET Theta= 1
UNET ZTol= 0.02
UNET ZSATol= 0.1
UNET MxIter= 20
UNET MaxInSteps= 20
UNET DtIC= 0
UNET DtMin= 0
UNET MaxCRTS= 20
UNET WFStab= 2
UNET SFStab= 1
UNET WFX= 1
UNET SFX= 1
UNET Convert EG Bridges=-1
UNET Use Existing IB Tables=-1
Instantaneous Interval=1HOUR
Write IC File= 0
Write Velocity= 0
Write Detailed= 0

--- P130-05-00.p01 (plan) ---

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Plan Title=FEMA Effective June 2007
Short Identifier=FEMAeff0607
Geom File= g01
Flow File= f01
Interactive Comp Mode
Encroach Param= -1, 0, 0, 0

--- P130-05-00.f02 (steady flow) ---

Flow Title= Floodway
Number of Profiles= 2
Profile Names=1PCT_100yr, 1PCTFloodway_100yrFW
River Rch & RM=P130-05-00,P130-05-00_0010,19522.4
    1392    1392
River Rch & RM=P130-05-00,P130-05-00_0010,18716.7
    1517    1517
River Rch & RM=P130-05-00,P130-05-00_0010,17747.2
    1646    1646
River Rch & RM=P130-05-00,P130-05-00_0010,16833.3
    1661    1661
River Rch & RM=P130-05-00,P130-05-00_0010,16737.1
    1744    1744
River Rch & RM=P130-05-00,P130-05-00_0010,16194.4
    1891    1891
River Rch & RM=P130-05-00,P130-05-00_0010,15285.8
    1961    1961
River Rch & RM=P130-05-00,P130-05-00_0010,14899.7
    1149    1149
River Rch & RM=P130-05-00,P130-05-00_0010,14427
    1986    1986
River Rch & RM=P130-05-00,P130-05-00_0010,11352.3
    2039    2039
River Rch & RM=P130-05-00,P130-05-00_0010,10788.7
    2085    2085
River Rch & RM=P130-05-00,P130-05-00_0010,10213.3
    2144    2144
River Rch & RM=P130-05-00,P130-05-00_0010,9642
    2213    2213
River Rch & RM=P130-05-00,P130-05-00_0010,8940.4
    2267    2267
River Rch & RM=P130-05-00,P130-05-00_0010,8406.6
    2334    2334
River Rch & RM=P130-05-00,P130-05-00_0010,7750.2
    2451    2451
River Rch & RM=P130-05-00,P130-05-00_0010,7086.8
    2521    2521
River Rch & RM=P130-05-00,P130-05-00_0010,6030.6
    2583    2583
River Rch & RM=P130-05-00,P130-05-00_0010,5496.7
    2706    2706
River Rch & RM=P130-05-00,P130-05-00_0010,4454.4
    2773    2773
River Rch & RM=P130-05-00,P130-05-00_0010,3909.8
    2851    2851
River Rch & RM=P130-05-00,P130-05-00_0010,3294.5
    2983    2983
River Rch & RM=P130-05-00,P130-05-00_0010,2288.3
    3063    3063
River Rch & RM=P130-05-00,P130-05-00_0010,1694.6
    3163    3163
Boundary for River Rch & Prof#=P130-05-00,P130-05-00_0010, 1
Up Type= 0
Dn Type= 3
Dn Slope= 0.00130
Boundary for River Rch & Prof#=P130-05-00,P130-05-00_0010, 2
Up Type= 0
Dn Type= 1
Dn Known WS=62.38

--- P130-05-00.f01 (steady flow) ---

Flow Title= FEMA Effective June 2007
Number of Profiles= 4
Profile Names=10PCT_10yr, 2PCT_50yr, 1PCT_100yr, 0.2PCT_500yr
River Rch & RM=P130-05-00,P130-05-00_0010,19522.4
     837    1204    1392    1912
River Rch & RM=P130-05-00,P130-05-00_0010,18716.7
     910    1312    1517    2088
River Rch & RM=P130-05-00,P130-05-00_0010,17747.2
     985    1423    1646    2268
River Rch & RM=P130-05-00,P130-05-00_0010,16833.3
     994    1436    1661    2290
River Rch & RM=P130-05-00,P130-05-00_0010,16737.1
    1041    1507    1744    2406
River Rch & RM=P130-05-00,P130-05-00_0010,16194.4
    1126    1633    1891    2613
River Rch & RM=P130-05-00,P130-05-00_0010,15285.8
    1166    1693    1961    2711
River Rch & RM=P130-05-00,P130-05-00_0010,14899.7
     940    1092    1149    2510
River Rch & RM=P130-05-00,P130-05-00_0010,14427
    1231    1737    1986    3007
River Rch & RM=P130-05-00,P130-05-00_0010,11352.3
    1263    1781    2039    3070
River Rch & RM=P130-05-00,P130-05-00_0010,10788.7
    1291    1821    2085    3126
River Rch & RM=P130-05-00,P130-05-00_0010,10213.3
    1327    1870    2144    3197
River Rch & RM=P130-05-00,P130-05-00_0010,9642
    1368    1928    2213    3278
River Rch & RM=P130-05-00,P130-05-00_0010,8940.4
    1401    1973    2267    3342
River Rch & RM=P130-05-00,P130-05-00_0010,8406.6
    1442    2030    2334    3421
River Rch & RM=P130-05-00,P130-05-00_0010,7750.2
    1512    2127    2451    3557
River Rch & RM=P130-05-00,P130-05-00_0010,7086.8
    1555    2187    2521    3639
River Rch & RM=P130-05-00,P130-05-00_0010,6030.6
    1592    2238    2583    3710
River Rch & RM=P130-05-00,P130-05-00_0010,5496.7
    1666    2341    2706    3851
River Rch & RM=P130-05-00,P130-05-00_0010,4454.4
    1707    2397    2773    3927
River Rch & RM=P130-05-00,P130-05-00_0010,3909.8
    1753    2462    2851    4015
River Rch & RM=P130-05-00,P130-05-00_0010,3294.5
    1833    2572    2983    4162
River Rch & RM=P130-05-00,P130-05-00_0010,2288.3
    1881    2639    3063    4252
River Rch & RM=P130-05-00,P130-05-00_0010,1694.6
    1941    2722    3163    4363
Boundary for River Rch & Prof#=P130-05-00,P130-05-00_0010, 1
Up Type= 0
Dn Type= 3
Dn Slope= 0.00130
Boundary for River Rch & Prof#=P130-05-00,P130-05-00_0010, 2
Up Type= 0
Dn Type= 3
Dn Slope= 0.00130
Boundary for River Rch & Prof#=P130-05-00,P130-05-00_0010, 3
Up Type= 0
Dn Type= 3
Dn Slope= 0.00130
Boundary for River Rch & Prof#=P130-05-00,P130-05-00_0010, 4
Up Type= 0
Dn Type= 3
Dn Slope= 0.00130

--- P130-05-00.g01 (geometry) ---

Geom Title=P130-05-00 June 2007
Version=Version 3.0.1  Mar 2001

River Reach=P130-05-00      ,P130-05-00_0010
Reach XY= 30
      3132315.04     13917168.34      3138414.75       13917429.
      3138732.25       13917189.       3139436.1     13916511.66
      3139808.88     13916467.09      3140116.82     13916564.33
        3140346.       13916568.      3141757.27     13916119.51
        3142061.       13915858.       3142276.5       13915525.
      3142526.25       13915260.      3143050.25       13914844.
      3143720.25       13914837.      3143870.89     13914749.09
        3144226.       13914680.        3144504.       13914495.
      3144710.75       13914556.       3144861.5       13914487.
      3145206.75       13914499.        3145853.       13914157.
       3145911.5       13914098.      3145889.25       13914068.
      3147061.76     13913730.04      3147478.25       13913243.
      3147659.41     13913166.82      3147894.42     13913168.85
      3148170.75       13913283.        3148307.       13913268.
      3148552.25       13913325.      3149198.25       13913252.

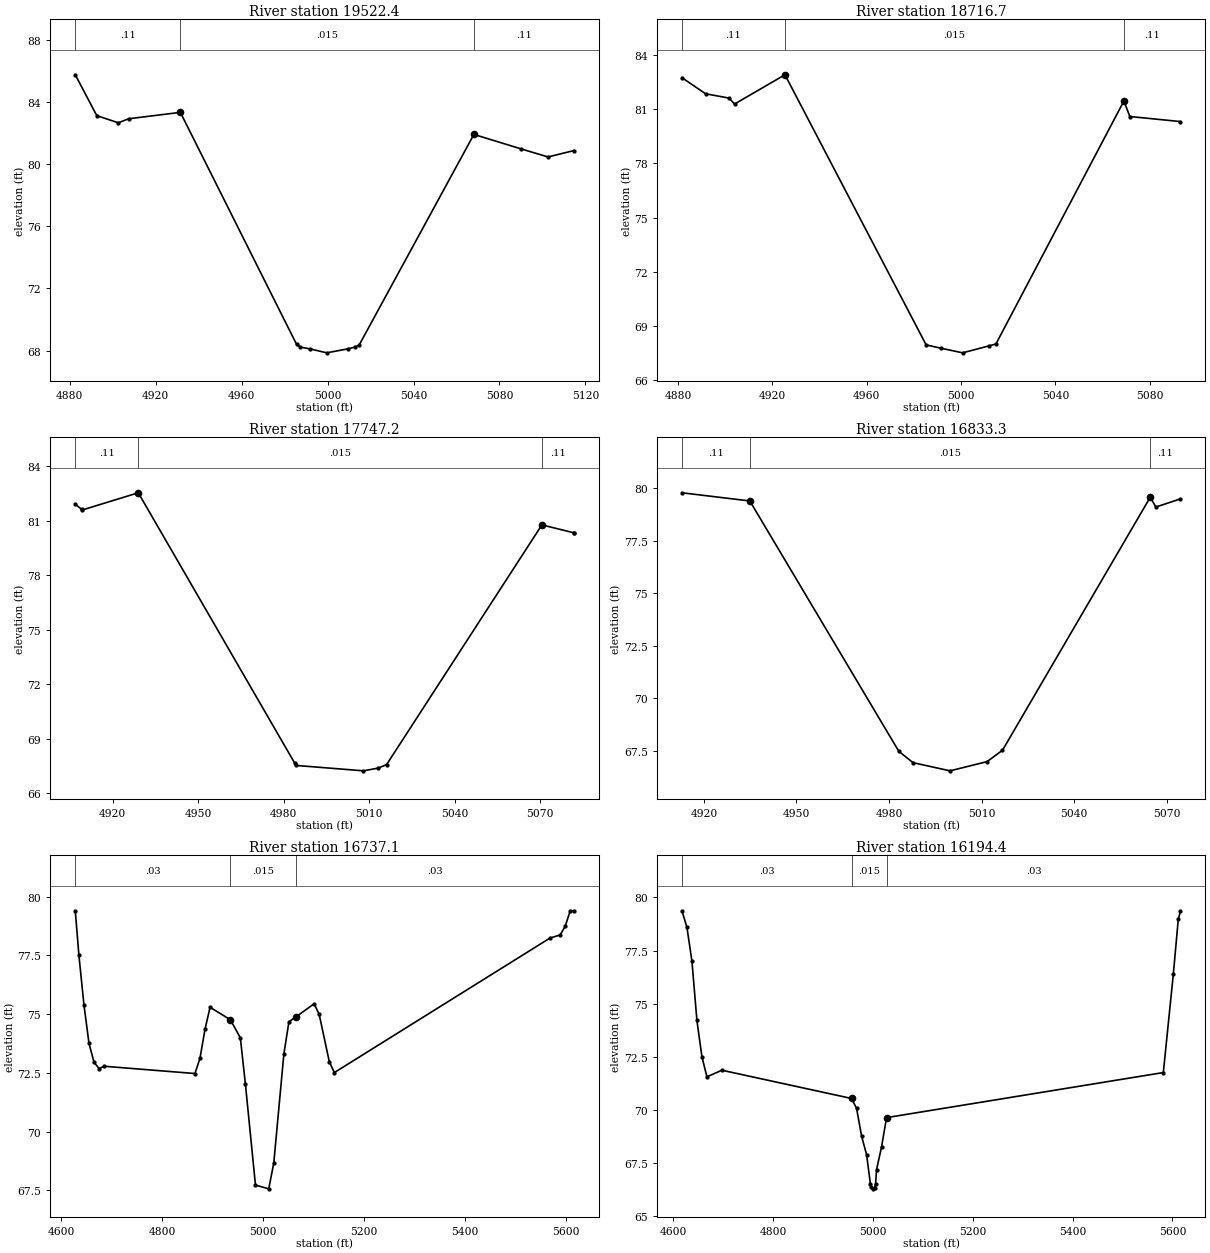
Type RM Length L Ch R = 1 ,19522.4 ,804.3,805.7,807.5
BEGIN DESCRIPTION:
Cross Section 19522.4
END DESCRIPTION:
XS GIS Cut Line= 2
      3132306.02     13917285.39      3132323.82     13917054.06
#Sta/Elev= 16
  4882.6   85.75  4892.6   83.12  4902.6   82.66  4907.5   82.92  4931.5   83.33
  4985.6   68.39  4987.3   68.22    4992    68.1  4999.6   67.85  5009.6   68.11
  5012.7   68.22  5014.7   68.35  5068.1   81.91  5089.8   80.99  5102.6   80.46
  5114.6   80.87
#Mann= 3 , 1 , 0
  4882.6     .11       0  4931.5    .015       0  5068.1     .11       0
Bank Sta=4931.5,5068.1
XS Rating Curve= 0
Exp/Cntr=.3,.1

Type RM Length L Ch R = 1 ,18716.7 ,968.9,969.5,964.6
BEGIN DESCRIPTION:
Cross Section 18716.7
END DESCRIPTION:
XS GIS Cut Line= 2
       3133108.7     13917322.47      3133128.75     13917111.93
#Sta/Elev= 13
  4881.6   82.74  4891.6   81.85  4901.6   81.61  4903.9   81.28  4925.3    82.9
  4985.2   67.95  4991.3   67.77  5000.7   67.51  5011.7   67.89  5014.8      68
  5069.1   81.45  5071.6   80.59  5093.1   80.31
#Mann= 3 , 1 , 0
  4881.6     .11       0  4925.3    .015       0  5069.1     .11       0
Bank Sta=4925.3,5069.1
XS Rating Curve= 0
Exp/Cntr=.3,.1

Type RM Length L Ch R = 1 ,17747.2 ,912.8,913.9,905.4
BEGIN DESCRIPTION:
Cross Section 17747.2
END DESCRIPTION:
XS GIS Cut Line= 2
      3134080.34     13917340.97      3134095.64     13917166.76
#Sta/Elev= 12
  4906.9   81.91  4909.2   81.62  4909.3   81.59    4929   82.54  4983.9   67.64
  4984.2   67.52    5008   67.22  5013.1   67.37  5016.1   67.56  5070.6   80.77
  5081.7   80.34  5081.8   80.33
#Mann= 3 , 1 , 0
  4906.9     .11       0    4929    .015       0  5070.6     .11       0
Bank Sta=4929,5070.6
XS Rating Curve= 0
Exp/Cntr=.3,.1

Type RM Length L Ch R = 1 ,16833.3 ,90.2,96.2,123
BEGIN DESCRIPTION:
Cross Section 16833.3
END DESCRIPTION:
XS GIS Cut Line= 2
      3134996.41     13917376.34      3135005.67     13917215.04
#Sta/Elev= 10
  4912.9   79.79  4934.9    79.4  4983.2   67.47  4987.8   66.93  4999.8   66.54
  5011.8   66.98  5016.8   67.52  5064.7   79.58  5066.5   79.11  5074.5    79.5
#Mann= 3 , 1 , 0
  4912.9     .11       0  4934.9    .015       0  5064.7     .11       0
Bank Sta=4934.9,5064.7
XS Rating Curve= 0
Exp/Cntr=.3,.1

Type RM Length L Ch R = 1 ,16737.1 ,542.7,542.7,542.7
BEGIN DESCRIPTION:
Cross Section 16737.1 - Interpolated
END DESCRIPTION:
XS GIS Cut Line= 5
      3135074.62     13917665.63      3135075.42     13917658.46
      3135098.18     13917282.91       3135086.8     13916725.28
      3135086.82      13916678.2
#Sta/Elev= 29
  4627.4    79.4  4634.6    77.5  4644.6   75.39  4654.6   73.75  4664.6   72.95
  4674.6   72.68  4684.6   72.78  4864.6   72.47  4874.6   73.12  4884.6   74.36
  4894.6   75.29  4934.9   74.76  4954.6   73.99  4964.6   72.03  4984.6   67.72
  5010.9   67.56  5020.9   68.66  5040.9    73.3  5050.9   74.67  5064.7   74.88
  5100.9   75.44  5110.9   74.99  5130.9   72.98  5140.9   72.51  5568.6   78.24
  5588.6   78.37  5598.6   78.74  5608.6    79.4  5615.7    79.4
#Mann= 3 , 1 , 0
  4627.4     .03       0  4934.9    .015       0  5064.7     .03       0
Bank Sta=4934.9,5064.7
XS Rating Curve= 0
Exp/Cntr=.3,.1

Type RM Length L Ch R = 1 ,16194.4 ,916,908.6,898.1
BEGIN DESCRIPTION:
Cross Section 16194.4 - Interpolated
END DESCRIPTION:
XS GIS Cut Line= 3
      3135621.83     13917700.68      3135665.72     13916757.05
      3135677.42     13916703.83
#Sta/Elev= 23
    4617   79.37    4627   78.59    4637      77    4647   74.21    4657   72.51
    4667   71.56    4697   71.87    4957   70.54    4967   70.07    4977   68.77
    4987    67.9  4994.8    66.5  4996.7   66.39  4999.9   66.29    5003   66.33
  5005.1   66.53    5007   67.19    5017   68.26    5027   69.64  5581.7   71.76
  5601.7   76.38  5611.7   78.98  5616.1   79.34
#Mann= 3 , 1 , 0
    4617     .03       0    4957    .015       0    5027     .03       0
Bank Sta=4957,5027
XS Rating Curve= 0
Exp/Cntr=.3,.1

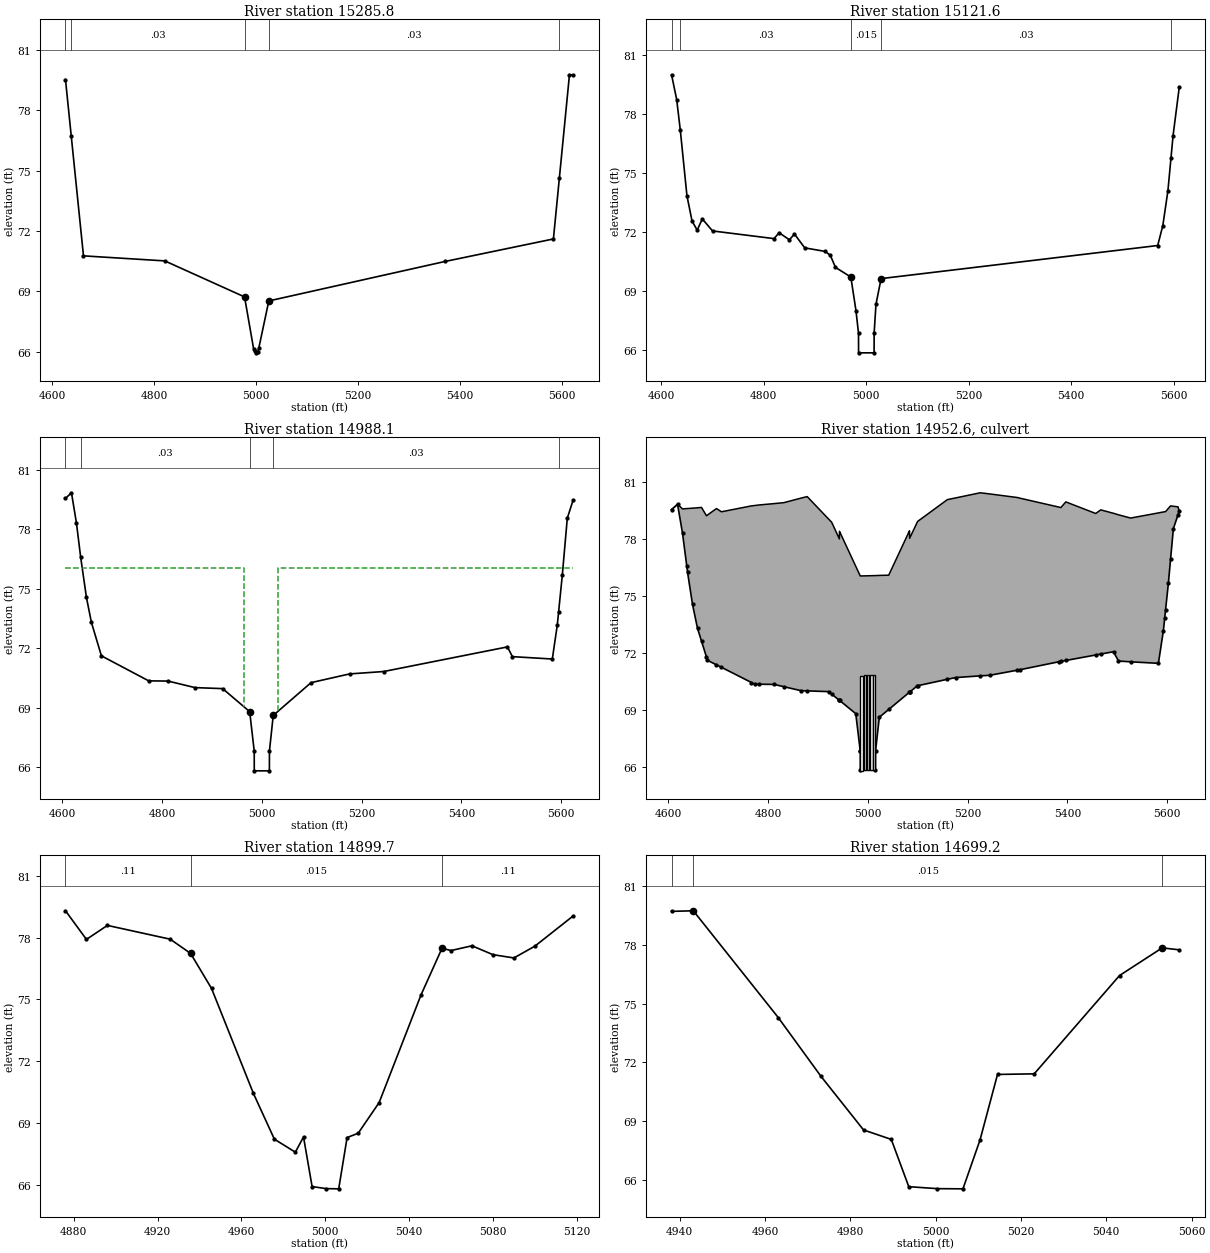
Type RM Length L Ch R = 1 ,15285.8 ,153,164.2,181.4
BEGIN DESCRIPTION:
Cross Section 15285.8
END DESCRIPTION:
XS GIS Cut Line= 3
      3136549.06     13917733.34      3136544.52     13916757.12
      3136544.43     13916736.28
#Sta/Elev= 17
  4625.7   79.52  4636.9   76.74    4661   70.76  4820.5   70.51  4977.1   68.72
  4994.8   66.15  4996.7   66.04  4999.9   65.94    5003   65.98  5005.1   66.18
  5024.6   68.51  5024.7   68.52  5370.3   70.48  5583.2    71.6  5594.9   74.63
  5614.7   79.76    5622   79.75
#Mann= 5 , 1 , 0
  4625.7     .14       0  4636.9     .03       0  4977.1    .015       0
  5024.6     .03       0  5594.9     .14       0
Bank Sta=4977.1,5024.6
XS Rating Curve= 0
Exp/Cntr=.3,.1

Type RM Length L Ch R = 1 ,15121.6 ,134.3,133.5,132.4
BEGIN DESCRIPTION:
Cross Section 15121.6 - Interpolated
END DESCRIPTION:
XS GIS Cut Line= 3
       3136683.7     13917745.59      3136710.52     13917377.41
       3136755.7       13916757.
#Sta/Elev= 30
  4619.8      80  4629.8   78.74  4636.9   77.18  4649.8   73.86  4659.8   72.57
  4669.8   72.11  4679.8   72.68  4699.8   72.07  4819.8   71.68  4829.8   71.98
  4849.8   71.62  4859.8   71.91  4879.8   71.21  4919.8   71.03  4929.8   70.83
  4939.8   70.22  4969.8   69.73  4979.8   68.03  4984.8   66.87  4984.9   65.88
  5015.2   65.88  5015.3   66.88  5018.9   68.35  5028.9   69.65  5568.9   71.33
  5578.9   72.34  5588.9   74.12  5594.9   75.79  5598.9   76.91    5611   79.37
#Mann= 5 , 1 , 0
  4619.8     .14       0  4636.9     .03       0  4969.8    .015       0
  5028.9     .03       0  5594.9     .14       0
Bank Sta=4969.8,5028.9
XS Rating Curve= 0
Exp/Cntr=.5,.3

Type RM Length L Ch R = 1 ,14988.1 ,88.4,88.4,88.4
BEGIN DESCRIPTION:
Upstream Section of Bridge/Culvert/Weir
END DESCRIPTION:
XS GIS Cut Line= 3
      3136759.77      13917755.2      3136783.46     13917657.87
      3136999.92     13916766.32
#Sta/Elev= 28
  4606.5   79.55  4618.5   79.83  4628.5    78.3  4636.9   76.59  4648.5   74.56
  4658.5    73.3  4678.5   71.62  4773.3   70.36  4812.1   70.35  4866.1   70.02
  4921.5   69.97  4975.7   68.81  4984.8   66.82  4984.9   65.83  5015.2   65.83
  5015.3   66.83  5022.9   68.62  5098.7   70.27  5175.9   70.71  5244.1   70.83
  5492.3   72.07  5502.3   71.58  5582.3   71.46  5592.3   73.18  5594.9   73.83
  5602.3   75.68  5612.3   78.55  5624.1   79.47
#Mann= 5 , 1 , 0
  4606.5     .14       0  4636.9     .03       0  4975.7    .015       0
  5022.9     .03       0  5594.9     .99       0
#XS Ineff= 2 , 0
       0    4965   76.06    5033       0   76.06
Permanent Ineff=
       F       F
Bank Sta=4975.7,5022.9
XS Rating Curve= 0
Exp/Cntr=.5,.3

Type RM Length L Ch R = 2 ,14952.6 ,,,
BEGIN DESCRIPTION:
DETENTION DAM
Structure ID: P35-7A
END DESCRIPTION:
Bridge Culvert--1,0,-1,-1, 0
Deck Dist Width WeirC Skew NumUp NumDn MinLoCord MaxHiCord MaxSubmerge Is_Ogee
10,51,3,0, 60, 60, , , .95, 0, 1,1,,
  4606.5  4618.5  4628.5  4636.9  4638.5  4648.5  4658.5  4666.5  4676.5  4678.5
  4696.5  4706.5  4766.7  4773.3  4782.4  4812.1  4831.5  4866.1  4878.3  4921.5
  4927.4 4942.89    4943 4943.11  4975.7  4984.7  4984.8  4984.9  5015.2  5015.3
  5022.9  5041.7 5083.39  5083.5 5083.61  5098.7  5099.6  5159.3  5175.9  5225.1
  5244.1  5299.8  5304.1  5382.3  5386.7  5396.7  5456.7  5466.7  5492.3  5502.3
  5526.7  5582.3  5592.3  5594.9  5596.7  5602.3  5606.7  5612.3  5621.6  5624.1
   79.55   79.84   79.59   79.61   79.61   79.63   79.65   79.67   79.23   79.27
   79.61   79.44   79.75   79.77    79.8   79.87   79.92   80.16   80.24   79.05
   78.89   78.01   78.41   78.41   76.57   76.06   76.06   76.06   76.08   76.08
   76.09    76.1   78.44   78.44   78.04   78.88   78.93   80.08   80.17   80.44
   80.38   80.19   80.16   79.69   79.66   79.96   79.35   79.54   79.36   79.28
   79.11   79.38   79.43   79.44   79.45   79.62   79.75   79.73    79.7   79.47
   79.55   79.83    78.3   76.59   76.26   74.56    73.3   72.63   71.79   71.62
   71.38   71.25   70.45   70.36   70.36   70.35   70.23   70.02   70.01   69.97
   69.84   69.51   69.51   69.51   68.81   66.84   66.82   65.83   65.83   66.83
   68.62   69.03   69.94   69.94   69.94   70.27   70.28   70.62   70.71    70.8
   70.83    71.1   71.12   71.54   71.56   71.61    71.9   71.95   72.07   71.58
   71.54   71.46   73.18   73.83   74.28   75.68   76.94   78.55   79.28   79.47
  4606.5  4618.5  4628.5  4636.9  4638.5  4648.5  4658.5  4666.5  4676.5  4678.5
  4696.5  4706.5  4766.7  4773.3  4782.4  4812.1  4831.5  4866.1  4878.3  4921.5
  4927.4 4942.89    4943 4943.11  4975.7  4984.7  4984.8  4984.9  5015.2  5015.3
  5022.9  5041.7 5083.39  5083.5 5083.61  5098.7  5099.6  5159.3  5175.9  5225.1
  5244.1  5299.8  5304.1  5382.3  5386.7  5396.7  5456.7  5466.7  5492.3  5502.3
  5526.7  5582.3  5592.3  5594.9  5596.7  5602.3  5606.7  5612.3  5621.6  5624.1
   79.55   79.84   79.59   79.61   79.61   79.63   79.65   79.67   79.23   79.27
   79.61   79.44   79.75   79.77    79.8   79.87   79.92   80.16   80.24   79.05
   78.89   78.01   78.41   78.41   76.57   76.06   76.06   76.06   76.08   76.08
   76.09    76.1   78.44   78.44   78.04   78.88   78.93   80.08   80.17   80.44
   80.38   80.19   80.16   79.69   79.66   79.96   79.35   79.54   79.36   79.28
   79.11   79.38   79.43   79.44   79.45   79.62   79.75   79.73    79.7   79.47
   79.55   79.83    78.3   76.59   76.26   74.56    73.3   72.63   71.79   71.62
   71.38   71.25   70.45   70.36   70.36   70.35   70.23   70.02   70.01   69.97
   69.84   69.51   69.51   69.51   68.81   66.84   66.82   65.83   65.83   66.83
   68.62   69.03   69.94   69.94   69.94   70.27   70.28   70.62   70.71    70.8
   70.83    71.1   71.12   71.54   71.56   71.61    71.9   71.95   72.07   71.58
   71.54   71.46   73.18   73.83   74.28   75.68   76.94   78.55   79.28   79.47
BR Coef= 1 , 0 , 0 ,1.25, 0 ,,,.8,-1,2,0,
WSPro=,,,, 1 ,,,, 0 ,,,, 0 ,,,,-1 ,-1 ,-1 , 0 , 0 , 0 , 0 , 0
Culvert=2,5,5,51,.015,.4,1,8,1,65.8,4987.6,65.81,4987.6,Culvert #1  , 0 ,10
Culvert Bottom n=.015
Culvert=2,5,5,51,.015,.4,1,8,1,65.83,4994.1,65.82,4994.1,Culvert #2  , 0 ,10
Culvert Bottom n=.015
Culvert=2,5,5,51,.015,.4,1,8,1,65.84,5000.7,65.87,5000.7,Culvert #3  , 0 ,10
Culvert Bottom n=.015
Culvert=2,5,5,51,.015,.4,1,8,1,65.83,5007,65.86,5007,Culvert #4  , 0 ,10
Culvert Bottom n=.015
Culvert=2,5,5,51,.015,.4,1,8,1,65.86,5012.4,65.83,5012.4,Culvert #5  , 0 ,10
Culvert Bottom n=.015
BR U #Sta/Elev= 60
  4606.5   79.55  4618.5   79.83  4628.5    78.3  4636.9   76.59  4638.5   76.26
  4648.5   74.56  4658.5    73.3  4666.5   72.63  4676.5   71.79  4678.5   71.62
  4696.5   71.38  4706.5   71.25  4766.7   70.45  4773.3   70.36  4782.4   70.36
  4812.1   70.35  4831.5   70.23  4866.1   70.02  4878.3   70.01  4921.5   69.97
  4927.4   69.84 4942.89   69.51    4943   69.51 4943.11   69.51  4975.7   68.81
  4984.7   66.84  4984.8   66.82  4984.9   65.83  5015.2   65.83  5015.3   66.83
  5022.9   68.62  5041.7   69.03 5083.39   69.94  5083.5   69.94 5083.61   69.94
  5098.7   70.27  5099.6   70.28  5159.3   70.62  5175.9   70.71  5225.1    70.8
  5244.1   70.83  5299.8    71.1  5304.1   71.12  5382.3   71.54  5386.7   71.56
  5396.7   71.61  5456.7    71.9  5466.7   71.95  5492.3   72.07  5502.3   71.58
  5526.7   71.54  5582.3   71.46  5592.3   73.18  5594.9   73.83  5596.7   74.28
  5602.3   75.68  5606.7   76.94  5612.3   78.55  5621.6   79.28  5624.1   79.47
BR U #Mann= 5
  4606.5     .14  4636.9     .03  4975.7    .015  5022.9     .03  5594.9     .99
BR U Banks=4975.7,5022.9
BR D #Sta/Elev= 60
  4606.5   79.55  4618.5   79.83  4628.5    78.3  4636.9   76.59  4638.5   76.26
  4648.5   74.56  4658.5    73.3  4666.5   72.63  4676.5   71.79  4678.5   71.62
  4696.5   71.38  4706.5   71.25  4766.7   70.45  4773.3   70.36  4782.4   70.36
  4812.1   70.35  4831.5   70.23  4866.1   70.02  4878.3   70.01  4921.5   69.97
  4927.4   69.84 4942.89   69.51    4943   69.51 4943.11   69.51  4975.7   68.81
  4984.7   66.84  4984.8   66.82  4984.9   65.83  5015.2   65.83  5015.3   66.83
  5022.9   68.62  5041.7   69.03 5083.39   69.94  5083.5   69.94 5083.61   69.94
  5098.7   70.27  5099.6   70.28  5159.3   70.62  5175.9   70.71  5225.1    70.8
  5244.1   70.83  5299.8    71.1  5304.1   71.12  5382.3   71.54  5386.7   71.56
  5396.7   71.61  5456.7    71.9  5466.7   71.95  5492.3   72.07  5502.3   71.58
  5526.7   71.54  5582.3   71.46  5592.3   73.18  5594.9   73.83  5596.7   74.28
  5602.3   75.68  5606.7   76.94  5612.3   78.55  5621.6   79.28  5624.1   79.47
BR D #Mann= 5
  4606.5     .14  4636.9     .03  4975.7    .015  5022.9     .03  5594.9     .99
BR D Banks=4975.7,5022.9
BC Design=,, 0 ,, 0 ,,,,,,

Type RM Length L Ch R = 1 ,14899.7 ,144.2,200.5,152
BEGIN DESCRIPTION:
Cross Section 14899.7 - Interpolated
END DESCRIPTION:
XS GIS Cut Line= 4
      3136909.53     13917497.59       3136919.6      13917439.3
      3136951.77     13917316.17      3136963.89     13917261.62
#Sta/Elev= 24
    4876    79.3    4886   77.91    4896   78.59    4926   77.92  4935.7   77.23
  4945.7   75.53  4965.7   70.43  4975.7   68.21  4985.7   67.58  4989.6   68.32
  4993.7   65.91  5000.4   65.81  5006.4    65.8  5010.4   68.29  5015.7    68.5
  5025.7   69.99  5045.7   75.22  5055.7   77.48    5060   77.37    5070    77.6
    5080   77.17    5090   77.01    5100   77.58  5118.3   79.05
#Mann= 3 , 1 , 0
    4876     .11       0  4935.7    .015       0  5055.7     .11       0
#XS Ineff= 2 , 0
       0    4925   76.08    5065       0   76.08
Permanent Ineff=
       F       F
Bank Sta=4935.7,5055.7
XS Rating Curve= 0
Exp/Cntr=.5,.3

Type RM Length L Ch R = 1 ,14699.2 ,270.6,272.2,345.6
BEGIN DESCRIPTION:
Cross Section 14699.2 - Interpolated
END DESCRIPTION:
XS GIS Cut Line= 2
      3137121.59     13917446.22      3137144.24     13917329.37
#Sta/Elev= 15
  4938.1    79.7  4943.2   79.73  4963.1   74.29  4973.1    71.3  4983.1   68.56
  4989.6   68.08  4993.7   65.67  5000.4   65.57  5006.4   65.56  5010.4   68.05
  5014.5   71.39  5023.1   71.42  5043.1   76.43  5053.1   77.84  5057.1   77.74
#Mann= 3 , 1 , 0
  4938.1     .11       0  4943.2    .015       0  5053.1     .11       0
Bank Sta=4943.2,5053.1
XS Rating Curve= 0
Exp/Cntr=.5,.3

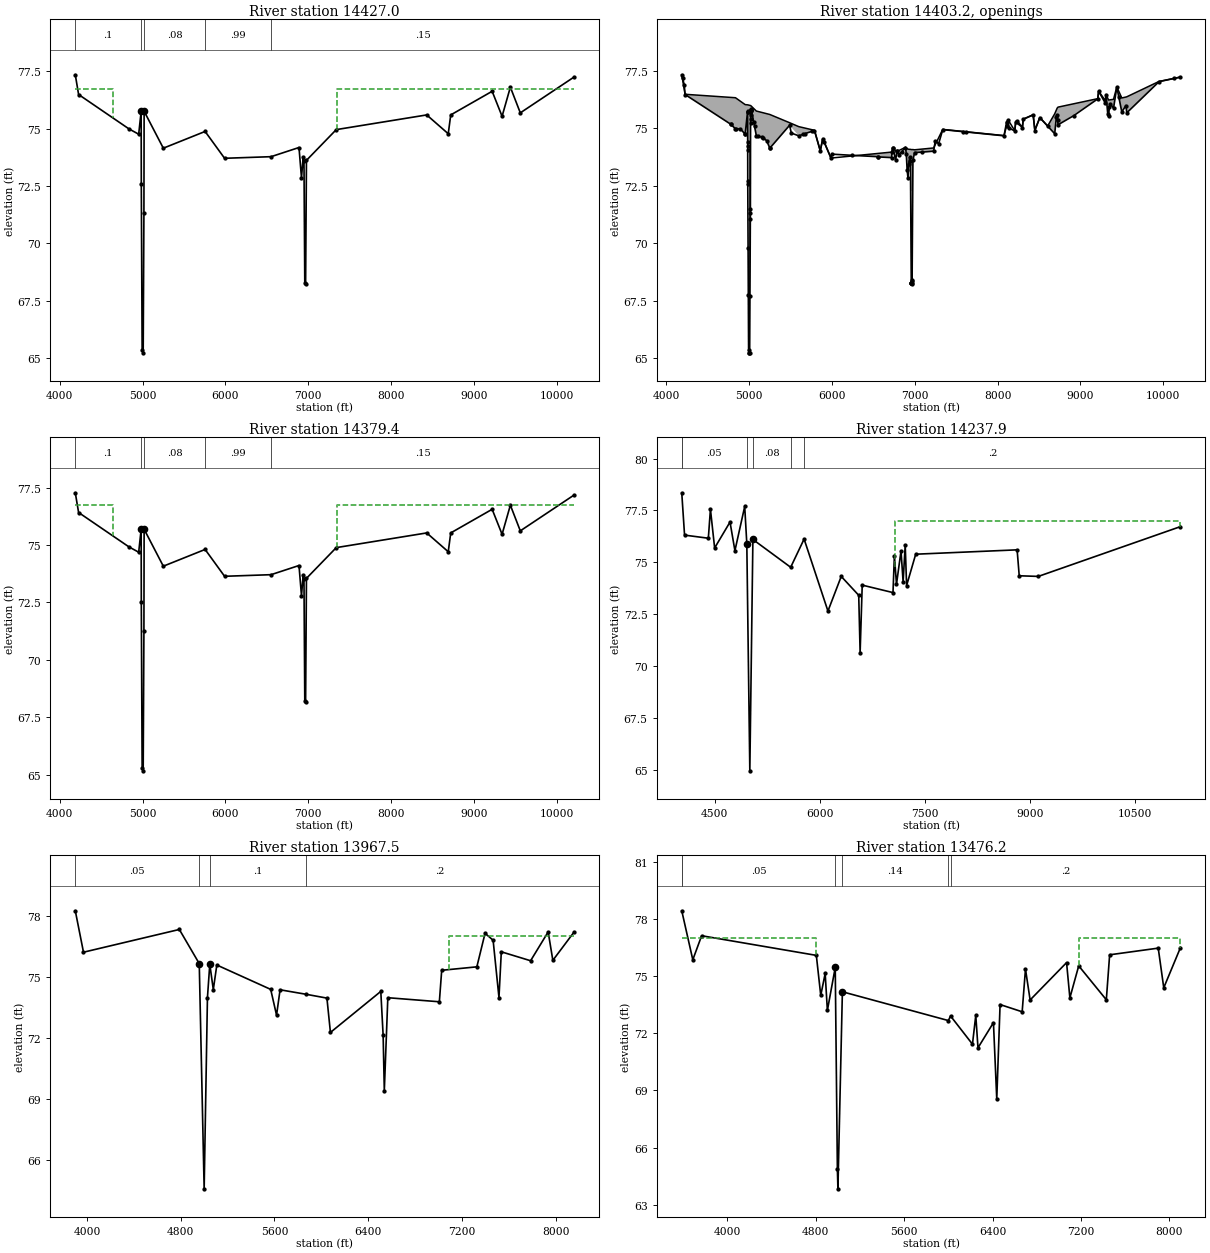
Type RM Length L Ch R = 1 ,14427.0 ,47.6,47.6,47.6
BEGIN DESCRIPTION:
Upstream Section of Bridge/Culvert/Weir
END DESCRIPTION:
XS GIS Cut Line= 6
      3137210.29     13918187.23      3137407.63      13917391.3
      3137468.83     13917127.29      3137829.87     13915626.26
      3136502.56     13914819.71      3134681.93      13914601.9
#Sta/Elev= 30
  4186.6   77.35  4226.6   76.49  4835.1   74.99  4952.2   74.76  4981.8   75.76
  4983.7   72.57  4993.7   65.34  5006.4   65.23  5015.2   71.34  5017.8   75.76
  5249.5   74.15    5754   74.88  5989.1   73.71  6550.3   73.78  6887.7   74.18
  6917.7   72.86  6937.7   73.75  6947.7    73.6  6957.5   68.28  6967.5   68.24
  6977.7   73.62  7337.7   74.96  8429.7    75.6  8689.7   74.78  8719.7    75.6
  9219.7   76.63  9339.7   75.54  9439.7   76.81  9559.7   75.69 10208.2   77.25
#Mann= 5 , 1 , 0
  4186.6      .1       0  4981.8    .015       0  5017.8     .08       0
    5754     .99       0  6550.3     .15       0
#XS Ineff= 2 , 0
       0    4647   76.75    7341       0   76.75
Permanent Ineff=
       F       F
Bank Sta=4981.8,5017.8
XS Rating Curve= 0
Exp/Cntr=.5,.3

Type RM Length L Ch R = 4 ,14403.2 ,,,
BEGIN DESCRIPTION:
LEE ROAD
Structure ID: P35-7,,,,
END DESCRIPTION:
Bridge Culvert--1,0,-1,-1, 0
Deck Dist Width WeirC Skew NumUp NumDn MinLoCord MaxHiCord MaxSubmerge Is_Ogee
10,27.6,2.6,0, 60, 60, , , .95, 0, 1,1,,
  4186.6  4226.6  4835.1  4952.2  4981.8 4982.81  5015.3 5017.49  5017.8  5024.1
  5086.9  5249.5  5489.1  5599.1  5789.1  5859.1  5889.1  5989.1  6719.1  6737.7
  6767.7  6787.6  6887.7  6917.7  6937.7  6947.7 6957.61  6957.7 6967.69  6967.8
  6977.7  6997.7  7227.7  7337.7  8077.7  8127.7  8207.7  8217.7  8299.7  8309.7
  8429.7  8449.7  8509.7  8604.6  8689.7  8719.7  8729.7  9209.7  9219.7  9299.7
  9309.7  9339.7  9359.7  9399.7  9439.7  9499.7  9549.7  9559.7  9949.3 10208.2
   77.34   76.49   76.34   76.04   76.03   76.03      76      76      76   75.98
   75.76   75.61   75.25   75.08   74.92   74.03   74.56   73.71   73.97   74.16
   74.03      74   74.18    74.1   74.09   74.09   74.08   74.08   74.08   74.08
   74.08   74.07   74.15   74.96   74.69   75.37    74.9   75.27   75.05   75.41
    75.6   74.92   75.48   75.11   75.64   75.89   75.93    76.3   76.63   76.22
   76.48   76.24   76.25   76.27   76.81   76.33   76.37   76.38   77.05   77.24
   77.34   76.48   74.98   74.75   75.75   74.23    74.2   75.22   75.75   75.86
   74.69   74.14   75.14   74.68   74.91   74.02   74.55    73.7   73.73   74.15
   73.62      74   74.17   72.85   73.74   73.59   68.27   72.28   72.28   68.39
   73.61   73.95   74.01   74.95   74.68   75.36   74.89   75.26   75.04    75.4
   75.59   74.91   75.47    75.1   74.77   75.59   75.16   76.29   76.62   76.11
   76.47   75.53   76.08   75.88    76.8   75.72      76   75.68   77.04   77.24
  4186.6  4226.6  4835.1  4952.2  4981.8 4982.81  5015.3 5017.49  5017.8  5024.1
  5086.9  5249.5  5489.1  5599.1  5789.1  5859.1  5889.1  5989.1  6719.1  6737.7
  6767.7  6787.6  6887.7  6917.7  6937.7  6947.7 6957.61  6957.7 6967.69  6967.8
  6977.7  6997.7  7227.7  7337.7  8077.7  8127.7  8207.7  8217.7  8299.7  8309.7
  8429.7  8449.7  8509.7  8604.6  8689.7  8719.7  8729.7  9209.7  9219.7  9299.7
  9309.7  9339.7  9359.7  9399.7  9439.7  9499.7  9549.7  9559.7  9949.3 10208.2
   77.34   76.49   76.34   76.04   76.03   76.03      76      76      76   75.98
   75.76   75.61   75.25   75.08   74.92   74.03   74.56   73.71   73.97   74.16
   74.03      74   74.18    74.1   74.09   74.09   74.08   74.08   74.08   74.08
   74.08   74.07   74.15   74.96   74.69   75.37    74.9   75.27   75.05   75.41
    75.6   74.92   75.48   75.11   75.64   75.89   75.93    76.3   76.63   76.22
   76.48   76.24   76.25   76.27   76.81   76.33   76.37   76.38   77.05   77.24
   77.29   76.43   74.93    74.7    75.7   74.18   74.15   75.17    75.7   75.81
   74.64   74.09   75.09   74.63   74.86   73.97    74.5   73.65   73.68    74.1
   73.57   73.95   74.12    72.8   73.69   73.54   68.22   72.23   72.23   68.34
   73.56    73.9   73.96    74.9   74.63   75.31   74.84   75.21   74.99   75.35
   75.54   74.86   75.42   75.05   74.72   75.54   75.11   76.24   76.57   76.06
   76.42   75.48   76.03   75.83   76.75   75.67   75.95   75.63   76.99   77.19
Pier Skew, UpSta & Num, DnSta & Num=  ,4999.8, 2 ,4999.8, 2 , 0 , 0 , 0 ,,
       1       1
   64.23   75.22
       1       1
   64.18   75.17
Abutment Skew #Up #Dn= , 2 , 2
  4980.9  4983.7
   75.73   72.56
  4980.9  4983.7
   75.68   72.51
Abutment Skew #Up #Dn= , 2 , 2
  5015.3 5020.19
    71.5   75.79
  5015.3 5020.19
   71.45   75.74
BR Coef= 1 , 1 , 0 ,1.25, 0 ,,,.8,0,2,0,
WSPro=,,,, 1 ,,,, 0 ,,,, 0 ,,,,-1 ,-1 ,-1 , 0 , 0 , 0 , 0 , 0
BR Coef= 1 , 1 , 0 ,1.25, 0 ,,,.8,0,2,0,
WSPro=,,,, 1 ,,,, 0 ,,,, 0 ,,,,-1 ,-1 ,-1 , 0 , 0 , 0 , 0 , 0
BC Mult= 3 ,3186.6,6311.87,3186.6,6311.87
BC Mult= 3 ,5666.03,11208.2,5666.03,11208.2
BR U #Sta/Elev= 131
  4186.6   77.34  4195.6   77.21  4216.6    76.9  4226.6   76.48  4775.4   75.19
  4775.6   75.19  4835.1   74.98  4836.4   74.98  4894.6   74.98  4950.6   74.76
  4952.2   74.75 4981.01   75.72  4981.1   75.73  4981.8   75.75 4982.59   74.42
  4982.7   74.24 4982.81   74.05  4983.6   72.73  4983.7   72.56  4987.1   69.78
  4989.6   67.74  4993.7   65.33  4999.8   65.23  5000.4   65.23  5006.4   65.22
  5010.4   67.71  5014.5   71.05  5015.2   71.33  5015.3    71.5 5017.49   75.22
  5017.6   75.41 5017.71    75.6  5017.8   75.75 5019.99   75.79  5020.1   75.79
  5020.2   75.79  5024.1   75.86  5055.2   75.28  5065.2   75.09  5086.9   74.69
  5111.8   74.66  5154.1   74.62  5171.1   74.58  5211.2   74.47  5249.5   74.14
  5249.8   74.14  5489.1   75.14  5509.1    74.8  5599.1   74.68    5650   74.74
  5677.6   74.78    5754   74.87  5789.1   74.91  5859.1   74.02  5889.1   74.55
  5907.6   74.39  5989.1    73.7  5999.1   73.88  6237.6   73.83  6550.3   73.77
  6557.6   73.76  6719.1   73.73  6727.7   73.98  6737.6   74.15  6737.7   74.15
  6767.7   73.62  6787.6      74  6787.7      74  6807.7   73.86  6841.4   73.99
  6887.7   74.17  6897.7   73.89  6907.7    73.2  6917.7   72.85  6927.7   73.45
  6937.7   73.74  6947.7   73.59  6957.5   68.27 6957.61   68.27  6957.7   68.27
  6957.8   68.27  6967.5   68.23  6967.6   68.28 6967.69   68.33  6967.8   68.39
  6977.7   73.61  6997.7   73.95  7091.4   73.97  7227.7   74.01  7247.7   74.46
  7287.7   74.33  7337.7   74.95  7581.4   74.86  7621.4   74.85  8077.7   74.68
  8107.7   75.26  8117.7   75.12  8127.7   75.36  8137.7   75.02  8207.7   74.89
  8217.7   75.26  8239.7   75.32  8299.7   75.04  8309.7    75.4  8429.7   75.59
  8449.7   74.91  8509.7   75.47  8604.6    75.1  8689.7   74.77  8709.7    75.5
  8719.7   75.59  8724.6   75.38  8729.7   75.16  8919.7   75.56  9209.7   76.29
  9219.7   76.62  9299.7   76.11  9309.7   76.47  9329.7   75.65  9339.7   75.53
  9349.7   75.94  9359.7   76.08  9399.7   75.88  9439.7    76.8  9464.6   76.35
  9499.7   75.72  9549.7      76  9559.7   75.68  9949.3   77.04 10134.6   77.18
 10208.2   77.24
BR U #Mann= 5
  4186.6      .1  4981.8    .015  5017.8     .08    5754     .99  6550.3     .15
BR U Banks=4981.8,5017.8
BR D #Sta/Elev= 131
  4186.6   77.29  4195.6   77.16  4216.6   76.85  4226.6   76.43  4775.4   75.14
  4775.6   75.14  4835.1   74.93  4836.4   74.93  4894.6   74.93  4950.6   74.71
  4952.2    74.7 4981.01   75.67  4981.1   75.68  4981.8    75.7 4982.59   74.37
  4982.7   74.19 4982.81      74  4983.6   72.68  4983.7   72.51  4987.1   69.73
  4989.6   67.69  4993.7   65.28  4999.8   65.18  5000.4   65.18  5006.4   65.17
  5010.4   67.66  5014.5      71  5015.2   71.28  5015.3   71.45 5017.49   75.17
  5017.6   75.36 5017.71   75.55  5017.8    75.7 5019.99   75.74  5020.1   75.74
  5020.2   75.74  5024.1   75.81  5055.2   75.23  5065.2   75.04  5086.9   74.64
  5111.8   74.61  5154.1   74.57  5171.1   74.53  5211.2   74.42  5249.5   74.09
  5249.8   74.09  5489.1   75.09  5509.1   74.75  5599.1   74.63    5650   74.69
  5677.6   74.73    5754   74.82  5789.1   74.86  5859.1   73.97  5889.1    74.5
  5907.6   74.34  5989.1   73.65  5999.1   73.83  6237.6   73.78  6550.3   73.72
  6557.6   73.71  6719.1   73.68  6727.7   73.93  6737.6    74.1  6737.7    74.1
  6767.7   73.57  6787.6   73.95  6787.7   73.95  6807.7   73.81  6841.4   73.94
  6887.7   74.12  6897.7   73.84  6907.7   73.15  6917.7    72.8  6927.7    73.4
  6937.7   73.69  6947.7   73.54  6957.5   68.22 6957.61   68.22  6957.7   68.22
  6957.8   68.22  6967.5   68.18  6967.6   68.23 6967.69   68.28  6967.8   68.34
  6977.7   73.56  6997.7    73.9  7091.4   73.92  7227.7   73.96  7247.7   74.41
  7287.7   74.28  7337.7    74.9  7581.4   74.81  7621.4    74.8  8077.7   74.63
  8107.7   75.21  8117.7   75.07  8127.7   75.31  8137.7   74.97  8207.7   74.84
  8217.7   75.21  8239.7   75.27  8299.7   74.99  8309.7   75.35  8429.7   75.54
  8449.7   74.86  8509.7   75.42  8604.6   75.05  8689.7   74.72  8709.7   75.45
  8719.7   75.54  8724.6   75.33  8729.7   75.11  8919.7   75.51  9209.7   76.24
  9219.7   76.57  9299.7   76.06  9309.7   76.42  9329.7    75.6  9339.7   75.48
  9349.7   75.89  9359.7   76.03  9399.7   75.83  9439.7   76.75  9464.6    76.3
  9499.7   75.67  9549.7   75.95  9559.7   75.63  9949.3   76.99 10134.6   77.13
 10208.2   77.19
BR D #Mann= 5
  4186.6      .1  4981.8    .015  5017.8     .08    5754     .99  6550.3     .15
BR D Banks=4981.8,5017.8
BC Design=,, 0 ,, 0 ,,,,,,

Type RM Length L Ch R = 1 ,14379.4 ,141.5,141.5,141.5
BEGIN DESCRIPTION:
Downstream Section of Bridge/Culvert/Weir
END DESCRIPTION:
XS GIS Cut Line= 6
      3137257.84     13918189.37      3137455.19     13917393.44
      3137516.39     13917129.43      3137877.43      13915628.4
      3136550.12     13914821.85      3134729.49     13914604.04
#Sta/Elev= 30
  4186.6   77.28  4226.6   76.42  4835.1   74.92  4952.2   74.69  4981.8   75.69
  4983.7    72.5  4993.7   65.27  5006.4   65.16  5015.2   71.27  5017.8   75.69
  5249.5   74.08    5754   74.81  5989.1   73.64  6550.3   73.71  6887.7   74.11
  6917.7   72.79  6937.7   73.68  6947.7   73.53  6957.5   68.21  6967.5   68.17
  6977.7   73.55  7337.7   74.89  8429.7   75.53  8689.7   74.71  8719.7   75.53
  9219.7   76.56  9339.7   75.47  9439.7   76.74  9559.7   75.62 10208.2   77.18
#Mann= 5 , 1 , 0
  4186.6      .1       0  4981.8    .015       0  5017.8     .08       0
    5754     .99       0  6550.3     .15       0
#XS Ineff= 2 , 0
       0    4647   76.75    7341       0   76.75
Permanent Ineff=
       F       F
Bank Sta=4981.8,5017.8
XS Rating Curve= 0
Exp/Cntr=.5,.3

Type RM Length L Ch R = 1 ,14237.9 ,240,270.4,279.3
BEGIN DESCRIPTION:
Cross Section 14237.9 - Interpolated
END DESCRIPTION:
XS GIS Cut Line= 6
      3137364.91     13918349.61      3137591.92     13917435.66
       3137624.8     13917199.95      3138025.86     13915348.31
       3136652.6     13914242.72      3134380.47     13913938.94
#Sta/Elev= 30
  4026.6   78.35  4066.6   76.31  4406.6   76.16  4436.6   77.56  4496.6   75.69
  4716.6   76.94  4786.6   75.56  4926.6   77.69  4956.6    75.9  4999.8   64.95
  5043.7    76.1  5583.8   74.76  5775.7   76.12  6116.6   72.65  6306.6   74.32
  6556.6   73.41  6576.6   70.65  6606.6    73.9  7046.6   73.54  7066.6   75.32
  7096.6   73.94  7161.2   75.55  7191.2   74.06  7221.2   75.83  7241.2   73.88
  7371.2   75.39  8821.2    75.6  8851.2   74.35  9124.2   74.32 11156.6   76.72
#Mann= 6 , 1 , 0
  4026.6      .2       0  4026.6     .05       0  4956.6     .03       0
  5043.7     .08       0  5583.8      .1       0  5775.7      .2       0
#XS Ineff= 2 , 0
       0    4927    77.6    7078       0      77
Permanent Ineff=
       F       F
Bank Sta=4956.6,5043.7
XS Rating Curve= 0
Exp/Cntr=.3,.1

Type RM Length L Ch R = 1 ,13967.5 ,484,491.3,496.1
BEGIN DESCRIPTION:
Cross Section 13967.5 - Interpolated
END DESCRIPTION:
XS GIS Cut Line= 5
      3137406.36     13918359.46      3137530.86     13918228.04
      3137814.44     13917882.21      3138120.72     13915009.52
       3137510.9     13914589.42
#Sta/Elev= 30
  3899.6   78.25  3969.6   76.21  4787.9   77.33  4957.9   75.65  4999.8   64.56
  5027.9   73.98  5047.9   75.62  5077.9   74.37  5107.9   75.58  5567.9   74.38
  5617.9   73.11  5647.9   74.36  5869.2   74.14  6047.9   73.95  6077.9   72.26
  6507.9   74.28  6527.9   72.11  6537.9    69.4  6567.9   73.97  7007.9   73.77
  7027.9   75.32  7327.9   75.49  7397.9   77.14  7466.8    76.8  7516.8   73.98
  7536.8   76.23  7786.8   75.79  7936.8   77.21  7976.8   75.81  8157.5    77.2
#Mann= 4 , 1 , 0
  3899.6     .05       0  4957.9    .035       0  5047.9      .1       0
  5869.2      .2       0
#XS Ineff= 2 , 0
       0    4805      77    7087       0      77
Permanent Ineff=
       F       F
Bank Sta=4957.9,5047.9
XS Rating Curve= 0
Exp/Cntr=.3,.1

Type RM Length L Ch R = 1 ,13476.2 ,1236.1,882.7,368.4
BEGIN DESCRIPTION:
Cross Section 13476.2
END DESCRIPTION:
XS GIS Cut Line= 6
      3138319.36     13918809.05      3138181.03     13918414.79
      3138273.41     13917871.94      3138412.08     13917131.16
      3138742.27     13915758.37      3137935.04     13914637.44
#Sta/Elev= 30
  3585.9   78.43  3685.9   75.86  3765.9   77.12  4804.4   76.09  4844.4   73.99
  4884.4   75.14  4904.4    73.2  4975.6   75.46    4995   64.86  4999.8   63.84
  5040.3   74.18  5999.6   72.67  6019.6   72.91    6218   71.43    6248   72.94
    6268   71.24    6408   72.56    6438   68.55    6468   73.51    6668   73.13
    6698   75.37    6740   73.75    7070   75.71    7100   73.86    7180   75.54
    7430   73.76    7460   76.12    7900   76.47    7950   74.39  8101.4    76.5
#Mann= 6 , 1 , 0
  3585.9      .2       0  3585.9     .05       0  4975.6    .035       0
  5040.3     .14       0  5999.6      .1       0  6019.6      .2       0
#XS Ineff= 2 , 0
       0    4800      77    7180       0      77
Permanent Ineff=
       F       F
Bank Sta=4975.6,5040.3
XS Rating Curve= 0
Exp/Cntr=.3,.1