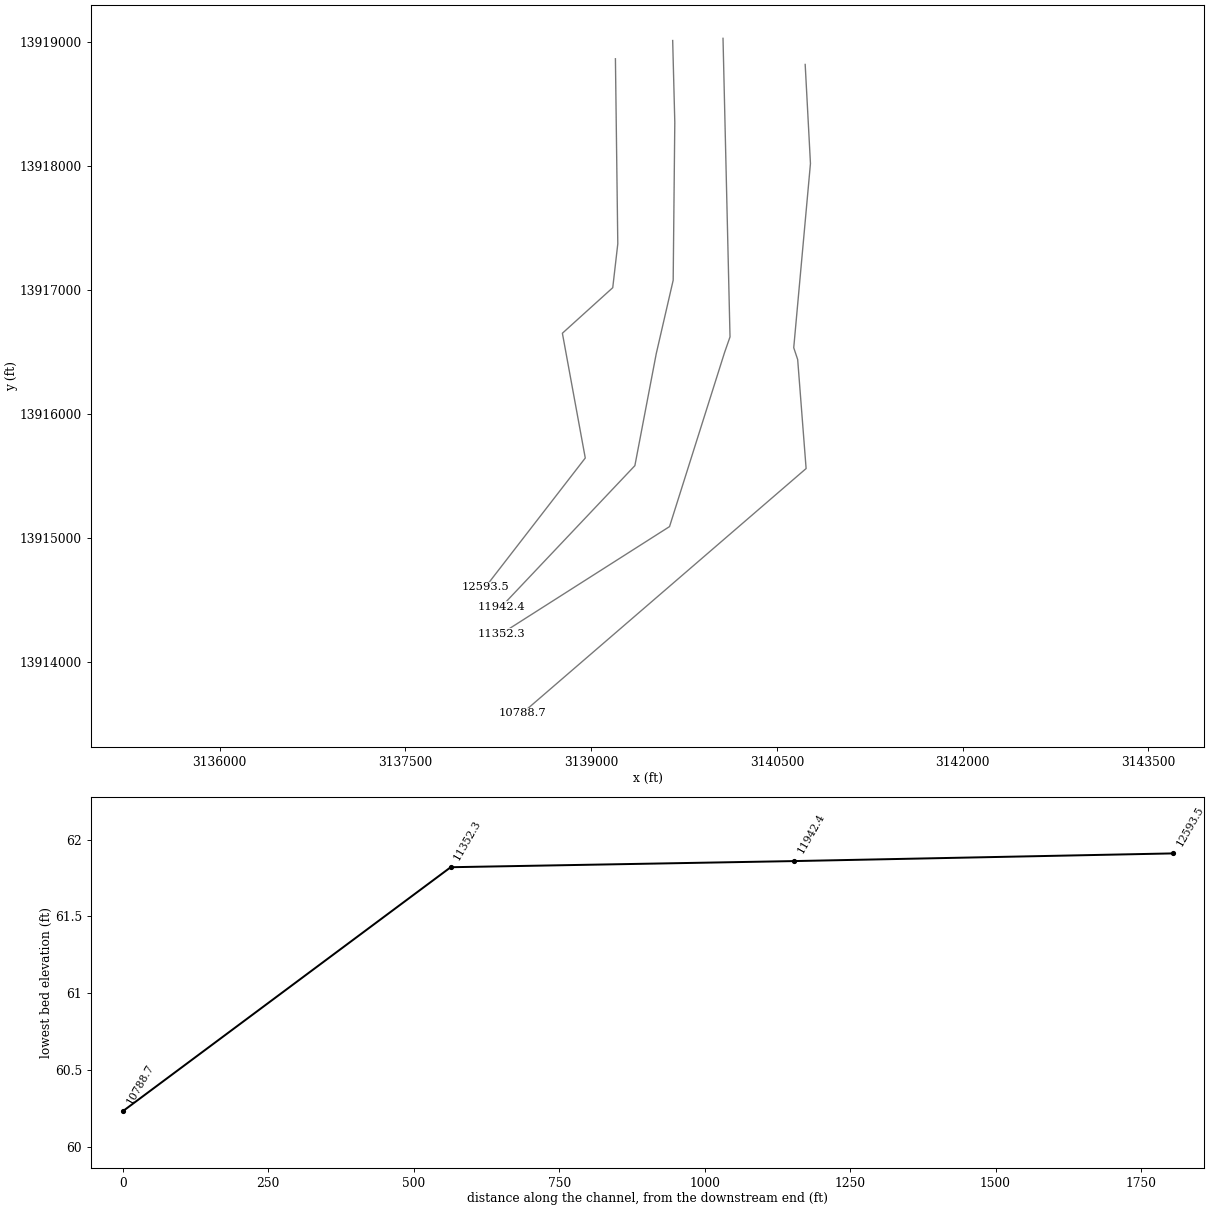
HEC-RAS study P130-05-00.PRJ: P130-05-00

--- P130-05-00.g01 (geometry) --- (continued)

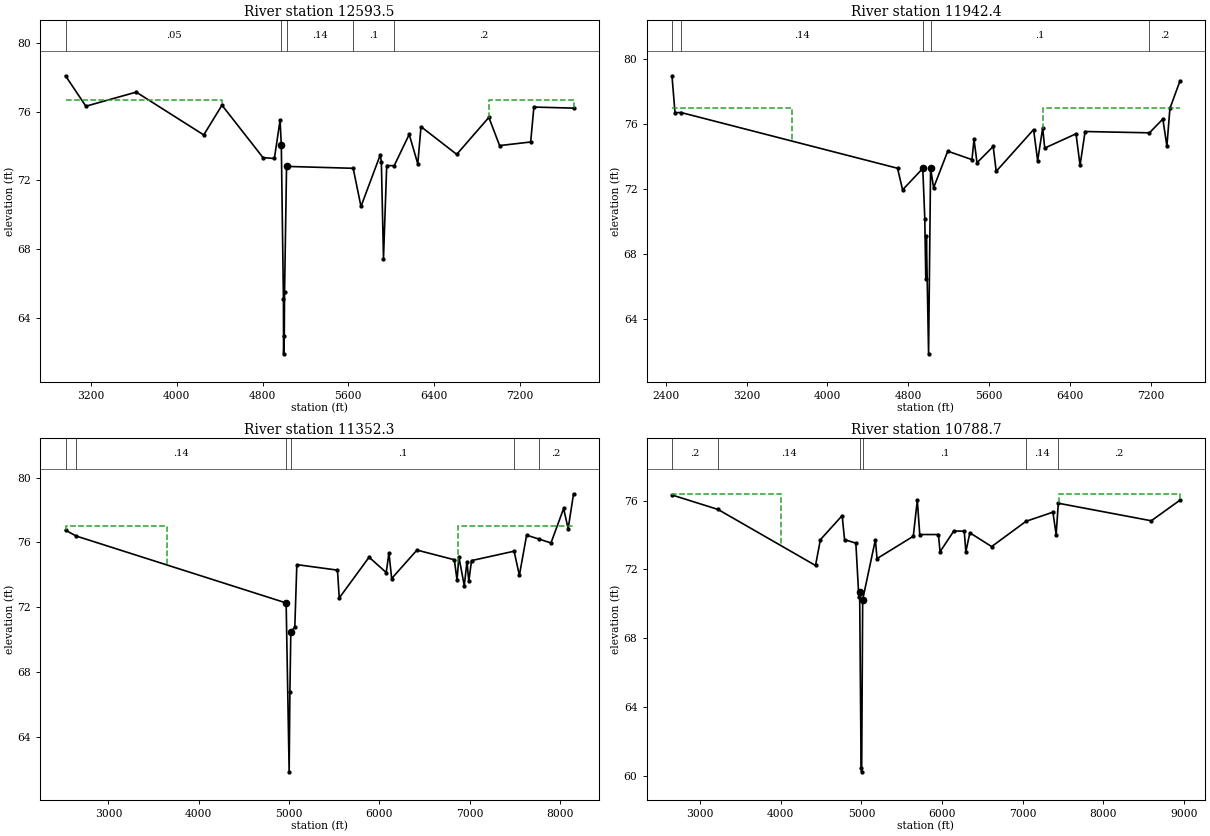
Type RM Length L Ch R = 1 ,12593.5 ,350.7,651.1,812.8
BEGIN DESCRIPTION:
Cross Section 12593.5
END DESCRIPTION:
XS GIS Cut Line= 6
      3139195.25     13918864.44      3139214.39      13917371.4
       3139173.6     13917017.84      3138766.94     13916650.41
       3138951.8     13915643.92       3138143.5      13914600.3
#Sta/Elev= 30
  2961.7   78.08  3151.7   76.31  3621.7   77.13  4251.7   74.64  4421.7   76.37
  4804.8   73.32  4910.7   73.27  4963.9    75.5  4975.4   74.03  4995.1   65.09
  4996.5   61.91    5003   62.92  5005.7    65.5  5024.3   72.81  5645.9    72.7
  5718.8   70.48  5898.8   73.48  5908.8   73.08  5928.8   67.45  5958.8   72.86
  6028.5   72.85  6168.8   74.67  6248.8   72.96  6278.8   75.12  6612.1   73.51
  6912.1   75.66  7012.1   74.02  7302.1   74.23  7332.1   76.26  7702.2    76.2
#Mann= 5 , 1 , 0
  2961.7     .05       0  4975.4    .035       0  5024.3     .14       0
  5645.9      .1       0  6028.5      .2       0
#XS Ineff= 2 , 0
       0    4420    76.7    6911       0    76.7
Permanent Ineff=
       F       F
Bank Sta=4975.4,5024.3
XS Rating Curve= 0
Exp/Cntr=.3,.1

Type RM Length L Ch R = 1 ,11942.4 ,454.2,590.1,560
BEGIN DESCRIPTION:
Cross Section 11942.4 - Interpolated
END DESCRIPTION:
XS GIS Cut Line= 6
      3139657.59     13919011.65      3139674.72     13918352.07
      3139661.64     13917078.07      3139525.08      13916486.3
      3139352.34      13915582.3      3138272.62     13914442.59
#Sta/Elev= 30
  2460.1   78.97  2490.1    76.7  2549.5   76.71    4694   73.28    4744   71.95
    4944   73.27    4964   70.17    4974   66.46  4979.8   69.09  5001.5   61.86
  5021.3   73.27  5051.3   72.08  5191.3   74.33  5431.3   73.81  5451.3   75.05
  5481.3   73.62  5641.3   74.62  5671.3   73.09  6041.6   75.66  6081.6   73.74
  6131.6   75.76  6151.6   74.52  6461.6    75.4  6501.6   73.46  6551.6   75.54
    7189   75.46  7321.6   76.31  7361.6   74.64  7391.6   76.96  7491.6   78.66
#Mann= 5 , 1 , 0
  2460.1      .2       0  2549.5     .14       0    4944     .04       0
  5021.3      .1       0    7189      .2       0
#XS Ineff= 2 , 0
       0    3650      77    6130       0      77
Permanent Ineff=
       F       F
Bank Sta=4944,5021.3
XS Rating Curve= 0
Exp/Cntr=.3,.1

Type RM Length L Ch R = 1 ,11352.3 ,538.6,563.6,441.4
BEGIN DESCRIPTION:
Cross Section 11352.3
END DESCRIPTION:
XS GIS Cut Line= 5
      3140064.07     13919029.27      3140120.64     13916620.91
      3140076.92     13916496.18       3139632.2     13915090.75
      3138273.96     13914226.63
#Sta/Elev= 30
  2525.2   76.76  2642.6    76.4  4968.1   72.26  5001.5   61.82  5009.6   66.76
    5020   70.46  5064.2   70.79  5086.4   74.63  5536.4   74.29  5556.4   72.57
  5886.4   75.09  6076.4   74.14  6106.4   75.36  6136.4   73.77  6416.4   75.53
  6830.5   74.93  6860.5   73.66  6880.5   75.11  6940.5   73.33  6970.5   74.82
  6990.5   73.59  7020.5   74.88  7491.9   75.46  7550.5   73.97  7630.5   76.45
  7762.3   76.22  7900.5   75.97  8040.5    78.1  8090.5   76.85  8150.3   79.01
#Mann= 6 , 1 , 0
  2525.2      .2       0  2642.6     .14       0  4968.1    .042       0
    5020      .1       0  7491.9     .14       0  7762.3      .2       0
#XS Ineff= 2 , 0
       0    3646      77    6875       0      77
Permanent Ineff=
       F       F
Bank Sta=4968.1,5020
XS Rating Curve= 0
Exp/Cntr=.5,.3

Type RM Length L Ch R = 1 ,10788.7 ,22,22,22
BEGIN DESCRIPTION:
Upstream Section of Bridge/Culvert/Weir
END DESCRIPTION:
XS GIS Cut Line= 6
      3140727.63     13918818.73      3140770.18     13918019.17
      3140635.18     13916533.69      3140666.99     13916438.17
       3140735.1     13915559.03       3138441.8     13913584.09
#Sta/Elev= 30
  2650.7   76.33  3221.3   75.49  4431.4   72.23  4491.4   73.73  4761.5   75.13
  4791.4   73.73  4931.5   73.53 4968.57   70.38 4978.47   70.71 4996.57   60.44
 5003.57   60.23 5016.07   70.24  5173.8   73.73  5193.9   72.63  5643.9   73.93
  5693.8   76.03  5723.8   74.03  5955.7   74.03  5975.7   73.03  6145.6   74.23
  6275.7   74.23  6295.7   73.03  6345.6   74.13  6615.7   73.33  7042.6    74.8
  7375.7   75.33  7415.7   74.03  7442.5   75.85  8595.7   74.83  8952.1   76.03
#Mann= 6 , 1 , 0
  2650.7      .2       0  3221.3     .14       0 4978.47    .042       0
 5016.07      .1       0  7042.6     .14       0  7442.5      .2       0
#XS Ineff= 2 , 0
       0    4000    76.4    7450       0    76.4
Permanent Ineff=
       F       F
Bank Sta=4978.47,5016.07
XS Rating Curve= 0
Exp/Cntr=.5,.3