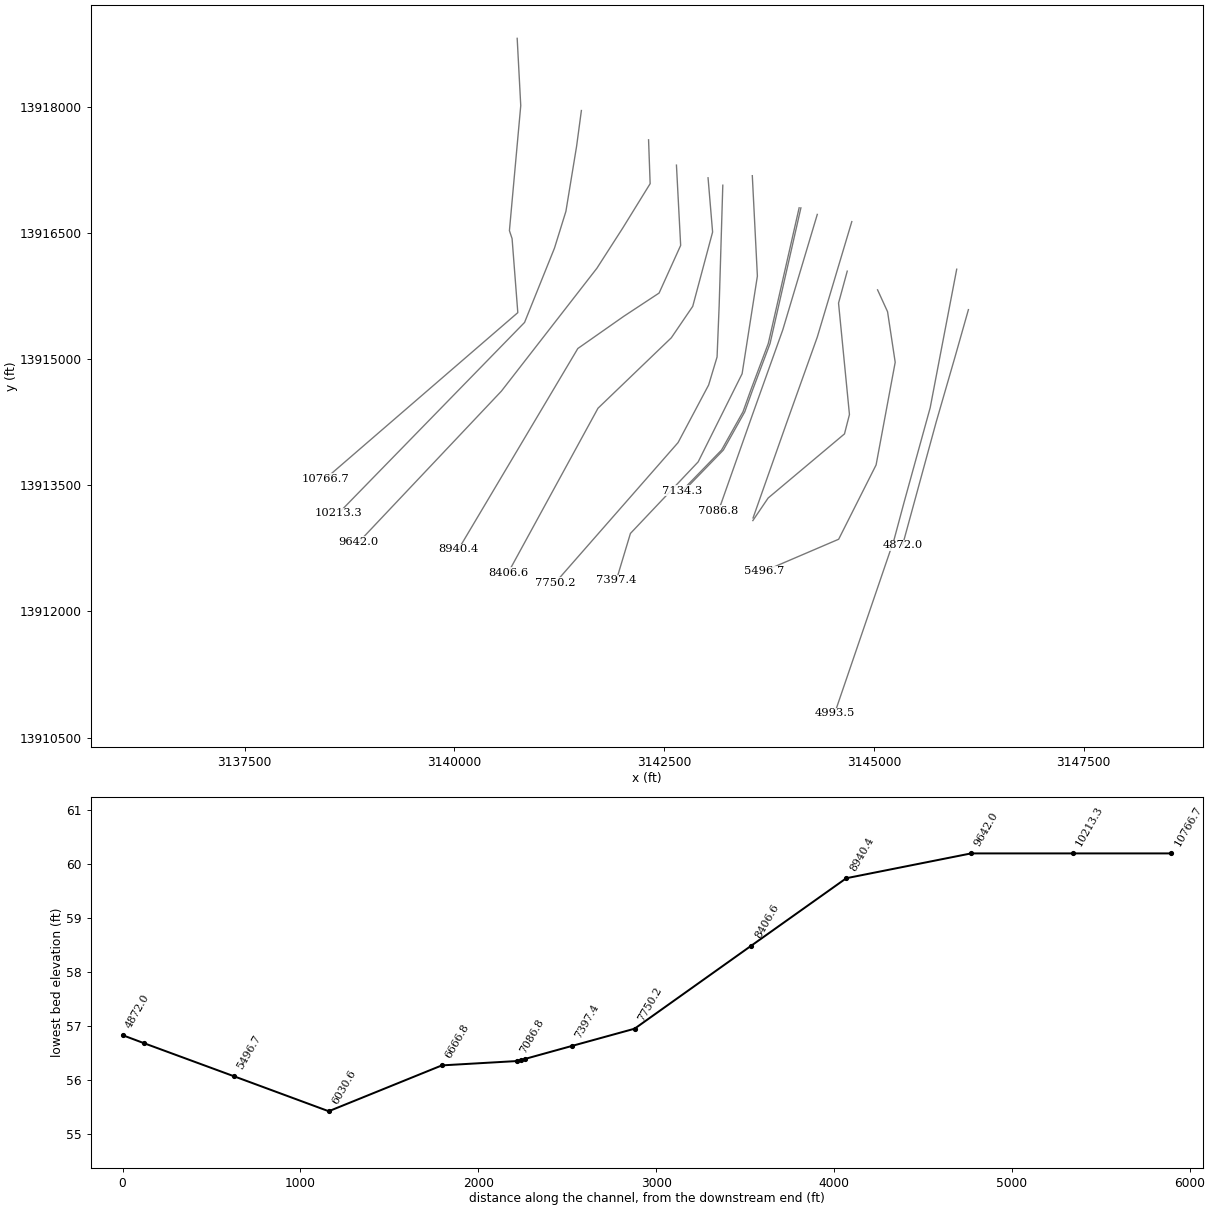
HEC-RAS study P130-05-00.PRJ: P130-05-00

--- P130-05-00.g01 (geometry) --- (continued)

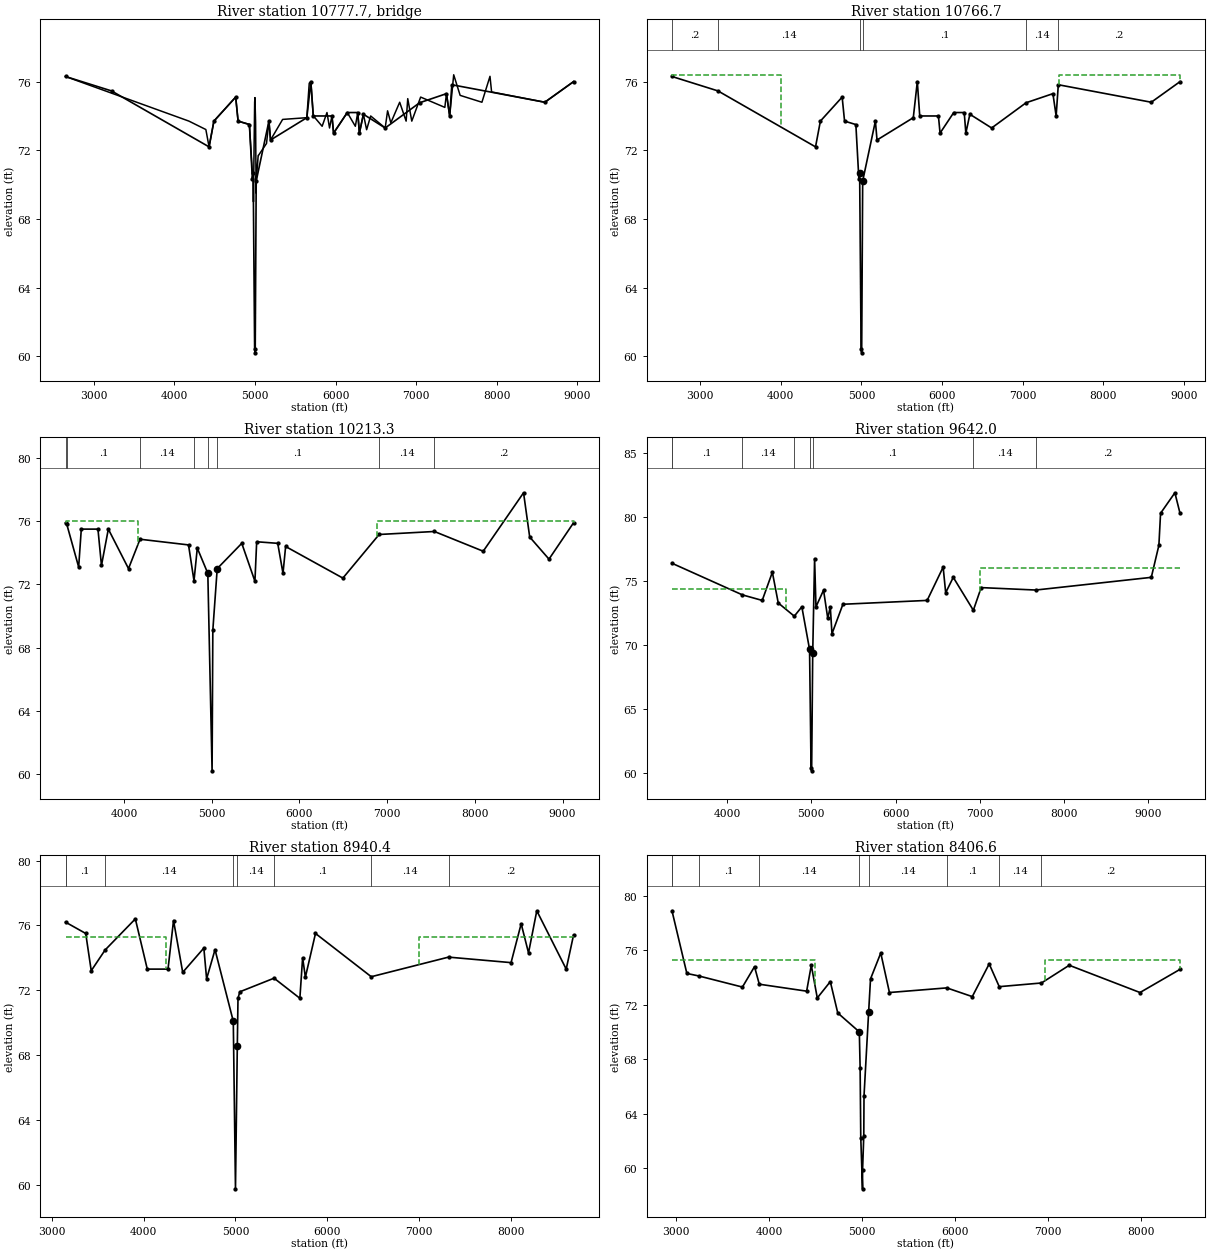
Type RM Length L Ch R = 3 ,10777.7 ,,,
BEGIN DESCRIPTION:
18" ARCHED PIPELINE - SKEW ANGLE OF 40 DEGREES
END DESCRIPTION:
Bridge Culvert--1,0,-1,-1, 0
Deck Dist Width WeirC Skew NumUp NumDn MinLoCord MaxHiCord MaxSubmerge Is_Ogee
10,2,2.6,0, 60, 60, , , .95, 0, 1,1,,
  2650.7  4181.5  4391.5  4431.4  4491.4  4761.5  4791.4  4931.5 4968.57 4978.47
 4981.67 4985.85 4985.94 4996.67 5000.67 5008.67 5011.14 5011.25 5014.67 5016.07
 5040.27  5043.9  5143.9  5173.8  5193.9  5343.8  5643.9  5673.8  5693.8  5723.8
  5833.8  5893.8  5925.6  5955.7  5975.7  6145.6  6245.7  6275.7  6295.7  6345.6
  6385.6  6435.6  6615.7  6645.6  6685.7  6795.6  6875.6  6895.6  6945.6  7055.6
  7355.7  7375.7  7415.7  7465.6  7545.6  7815.6  7915.7  7935.6  8595.6  8952.1
    76.3    73.7   73.21    72.2    73.7    75.1    73.7   73.51   70.68   70.69
      69   70.75   70.79    74.8   75.07    73.6   71.91   71.84    69.5   70.22
    71.7    71.7    72.4    73.7    72.6    73.8    73.9   75.91      76   74.01
    73.4    74.2    73.3      74      73    74.2    73.4    74.2      73    74.1
    73.2      74    73.3    74.3    73.6    74.8    73.7   75.01    73.7    75.1
    74.5    75.3      74    76.4    75.2    74.8   76.31    75.4    74.8      76
    76.3    73.7    73.2    72.2    73.7    75.1    73.7    73.5   70.35   70.68
   68.98   66.76   69.29    73.3   73.57    72.1   70.41   66.64   69.17   70.21
   70.69    71.7    72.4    73.7    72.6    73.8    73.9    75.9      76      74
    73.4    74.2    73.3      74      73    74.2    73.4    74.2      73    74.1
    73.2      74    73.3   74.29    73.6    74.8    73.7      75    73.7    75.1
    74.5    75.3      74    76.4    75.2    74.8    76.3    75.4    74.8      76
  2650.7  4181.5  4391.5  4431.4  4491.4  4761.5  4791.4  4931.5 4968.57 4978.47
 4981.67 4985.85 4985.94 4996.67 5000.67 5008.67 5011.14 5011.25 5014.67 5016.07
 5040.27  5043.9  5143.9  5173.8  5193.9  5343.8  5643.9  5673.8  5693.8  5723.8
  5833.8  5893.8  5925.6  5955.7  5975.7  6145.6  6245.7  6275.7  6295.7  6345.6
  6385.6  6435.6  6615.7  6645.6  6685.7  6795.6  6875.6  6895.6  6945.6  7055.6
  7355.7  7375.7  7415.7  7465.6  7545.6  7815.6  7915.7  7935.6  8595.6  8952.1
    76.3    73.7   73.21    72.2    73.7    75.1    73.7   73.51   70.68   70.69
      69   70.75   70.79    74.8   75.07    73.6   71.91   71.84    69.5   70.22
    71.7    71.7    72.4    73.7    72.6    73.8    73.9   75.91      76   74.01
    73.4    74.2    73.3      74      73    74.2    73.4    74.2      73    74.1
    73.2      74    73.3    74.3    73.6    74.8    73.7   75.01    73.7    75.1
    74.5    75.3      74    76.4    75.2    74.8   76.31    75.4    74.8      76
    76.3    73.7    73.2    72.2    73.7    75.1    73.7    73.5   70.35   70.68
   68.98   66.76   69.29    73.3   73.57    72.1   70.41   66.64   69.17   70.21
   70.69    71.7    72.4    73.7    72.6    73.8    73.9    75.9      76      74
    73.4    74.2    73.3      74      73    74.2    73.4    74.2      73    74.1
    73.2      74    73.3   74.29    73.6    74.8    73.7      75    73.7    75.1
    74.5    75.3      74    76.4    75.2    74.8    76.3    75.4    74.8      76
BR Coef= 1 , 1 , 0 ,1.25, 0 ,,,.8,0,2,0,
WSPro=,,,, 1 ,,,, 0 ,,,, 0 ,,,,-1 ,-1 ,-1 , 0 , 0 , 0 , 0 , 0
BR U #Sta/Elev= 30
  2650.7    76.3  3221.3   75.46  4431.4    72.2  4491.4    73.7  4761.5    75.1
  4791.4    73.7  4931.5    73.5 4968.57   70.35 4978.47   70.68 4996.57   60.41
 5003.57    60.2 5016.07   70.21  5173.8    73.7  5193.9    72.6  5643.9    73.9
  5693.8      76  5723.8      74  5955.7      74  5975.7      73  6145.6    74.2
  6275.7    74.2  6295.7      73  6345.6    74.1  6615.7    73.3  7042.6   74.77
  7375.7    75.3  7415.7      74  7442.5   75.82  8595.7    74.8  8952.1      76
BR U #Mann= 6
  2650.7      .2  3221.3     .14 4978.47    .045 5016.07      .1  7042.6     .14
  7442.5      .2
BR U Banks=4978.47,5016.07
BR D #Sta/Elev= 30
  2650.7    76.3  3221.3   75.46  4431.4    72.2  4491.4    73.7  4761.5    75.1
  4791.4    73.7  4931.5    73.5 4968.57   70.35 4978.47   70.68 4996.57   60.41
 5003.57    60.2 5016.07   70.21  5173.8    73.7  5193.9    72.6  5643.9    73.9
  5693.8      76  5723.8      74  5955.7      74  5975.7      73  6145.6    74.2
  6275.7    74.2  6295.7      73  6345.6    74.1  6615.7    73.3  7042.6   74.77
  7375.7    75.3  7415.7      74  7442.5   75.82  8595.7    74.8  8952.1      76
BR D #Mann= 6
  2650.7      .2  3221.3     .14 4978.47    .045 5016.07      .1  7042.6     .14
  7442.5      .2
BR D Banks=4978.47,5016.07
BC Design=,, 0 ,, 0 ,,,,,,

Type RM Length L Ch R = 1 ,10766.7 ,553.4,553.4,553.4
BEGIN DESCRIPTION:
Downstream Section of Bridge/Culvert/Weir
END DESCRIPTION:
XS GIS Cut Line= 6
      3140748.21     13918810.97      3140790.76     13918011.41
      3140655.76     13916525.93      3140687.57     13916430.41
      3140755.68     13915551.27      3138462.38     13913576.33
#Sta/Elev= 30
  2650.7    76.3  3221.3   75.46  4431.4    72.2  4491.4    73.7  4761.5    75.1
  4791.4    73.7  4931.5    73.5 4968.57   70.35 4978.47   70.68 4996.57   60.41
 5003.57    60.2 5016.07   70.21  5173.8    73.7  5193.9    72.6  5643.9    73.9
  5693.8      76  5723.8      74  5955.7      74  5975.7      73  6145.6    74.2
  6275.7    74.2  6295.7      73  6345.6    74.1  6615.7    73.3  7042.6   74.77
  7375.7    75.3  7415.7      74  7442.5   75.82  8595.7    74.8  8952.1      76
#Mann= 6 , 1 , 0
  2650.7      .2       0  3221.3     .14       0 4978.47    .042       0
 5016.07      .1       0  7042.6     .14       0  7442.5      .2       0
#XS Ineff= 2 , 0
       0    4000    76.4    7450       0    76.4
Permanent Ineff=
       F       F
Bank Sta=4978.47,5016.07
XS Rating Curve= 0
Exp/Cntr=.5,.3

Type RM Length L Ch R = 1 ,10213.3 ,677.9,571.3,400.9
BEGIN DESCRIPTION:
Cross Section 10213.3 - Interpolated
END DESCRIPTION:
XS GIS Cut Line= 6
      3141513.32     13917953.17      3141456.29     13917528.72
      3141328.84     13916754.87      3141192.87     13916318.43
      3140836.28     13915434.89      3138620.35     13913167.99
#Sta/Elev= 30
  3332.3    75.9  3345.2   75.84  3482.3    73.1  3512.3    75.5  3702.3    75.5
  3742.3    73.2  3820.6    75.5  4050.6      73    4182   74.86  4734.9    74.5
  4797.3   72.23  4834.9    74.3  4954.9    72.7  5003.5    60.2    5012    69.1
    5062      73    5342    74.6    5492    72.2    5512    74.7    5752    74.6
    5812    72.7    5842    74.4  6494.8    72.4  6908.1   75.16  7537.8   75.35
  8094.8    74.1  8554.8    77.8  8624.8      75  8844.8    73.6  9124.8    75.9
#Mann= 8 , 1 , 0
  3332.3      .2       0  3345.2      .1       0    4182     .14       0
  4797.3      .1       0  4954.9    .042       0    5062      .1       0
  6908.1     .14       0  7537.8      .2       0
#XS Ineff= 2 , 0
       0    4157      76    6883       0      76
Permanent Ineff=
       F       F
Bank Sta=4954.9,5062
XS Rating Curve= 0
Exp/Cntr=.3,.1

Type RM Length L Ch R = 1 ,9642.0  ,853.4,701.6,697.5
BEGIN DESCRIPTION:
Cross Section  9642.0
END DESCRIPTION:
XS GIS Cut Line= 6
      3142313.78     13917605.07      3142332.62     13917083.88
      3142006.09     13916556.41       3141698.4     13916079.18
      3140560.55     13914618.71       3138861.2     13912824.95
#Sta/Elev= 30
  3345.2    76.4    4182   73.93  4416.7    73.5  4537.1    75.7  4607.1    73.3
  4797.3   72.27  4887.1      73  4978.7   69.68  4996.5   60.41  5003.5    60.2
  5016.2   69.36  5038.6   76.76  5054.9      73  5144.9    74.3  5194.9    72.1
  5224.9      73  5244.9    70.9  5374.9    73.2  6374.9    73.5  6564.9    76.1
  6594.9    74.1  6684.9    75.3  6923.5   72.73  7016.3    74.5  7664.6   74.31
  9036.3    75.3  9126.3    77.8  9146.3    80.3  9316.3    81.9  9377.2    80.3
#Mann= 8 , 1 , 0
  3345.2      .2       0  3345.2      .1       0    4182     .14       0
  4797.3      .1       0  4978.7    .043       0  5016.2      .1       0
  6923.5     .14       0  7664.6      .2       0
#XS Ineff= 2 , 0
       0    4695    74.4    7000       0      76
Permanent Ineff=
       F       F
Bank Sta=4978.7,5016.2
XS Rating Curve= 0
Exp/Cntr=.3,.1

Type RM Length L Ch R = 1 ,8940.4  ,484.1,533.8,567.8
BEGIN DESCRIPTION:
Cross Section  8940.4
END DESCRIPTION:
XS GIS Cut Line= 6
      3142646.01     13917304.24      3142696.23     13916350.04
      3142439.37     13915784.05      3142018.65     13915507.76
      3141470.91     13915124.87      3140047.52     13912736.94
#Sta/Elev= 30
  3150.1    76.2  3370.1    75.5  3430.1    73.2    3581   74.48  3910.1    76.4
  4040.1    73.3  4265.6    73.3  4325.6    76.3  4425.6    73.1  4655.6    74.6
  4685.6    72.7  4777.2    74.5    4976   70.08  4999.8   59.74  5019.7   68.55
  5027.2    71.5  5047.2    71.9  5419.7   72.74  5700.5    71.5  5730.5      74
  5760.5    72.8  5870.5    75.5  6477.5   72.83  7318.3   74.04  7998.8    73.7
  8108.8    76.1  8188.8    74.3  8278.8    76.9  8598.8    73.3  8678.8    75.4
#Mann= 8 , 1 , 0
  3150.1      .2       0  3150.1      .1       0    3581     .14       0
    4976    .045       0  5019.7     .14       0  5419.7      .1       0
  6477.5     .14       0  7318.3      .2       0
#XS Ineff= 2 , 0
       0    4243    75.3    7000       0    75.3
Permanent Ineff=
       F       F
Bank Sta=4976,5019.7
XS Rating Curve= 0
Exp/Cntr=.3,.1

Type RM Length L Ch R = 1 ,8406.6  ,538.4,656.4,828.2
BEGIN DESCRIPTION:
Cross Section  8406.6 - Interpolated XS 8406.6
END DESCRIPTION:
XS GIS Cut Line= 6
      3143022.67     13917153.58      3143076.83     13916509.06
      3142840.12     13915625.96      3142585.21     13915252.69
      3141711.21      13914415.1      3140640.04     13912459.07
#Sta/Elev= 30
  2956.4    78.9  3116.4    74.3  3247.9   74.11  3713.2    73.3  3843.2    74.8
  3894.5   73.51  4403.2      73  4453.2    74.9  4517.5    72.5  4657.5    73.7
  4737.5    71.4  4969.2   70.01  4977.8   67.36  4984.7   62.25  5003.6   58.49
  5004.2    59.9  5017.1   62.39  5019.5    65.3  5069.5    71.5  5089.5    73.9
  5199.5    75.8  5292.7    72.9  5908.9   73.24  6182.7    72.6  6364.4      75
  6472.4   73.33    6926    73.6  7224.4    74.9  7984.4    72.9  8414.5    74.6
#Mann= 9 , 1 , 0
  2956.4      .2       0  2956.4     .14       0  3247.9      .1       0
  3894.5     .14       0  4969.2    .045       0  5069.5     .14       0
  5908.9      .1       0  6472.4     .14       0    6926      .2       0
#XS Ineff= 2 , 0
       0    4494    75.3    6962       0    75.3
Permanent Ineff=
       F       F
Bank Sta=4969.2,5069.5
XS Rating Curve= 0
Exp/Cntr=.3,.1

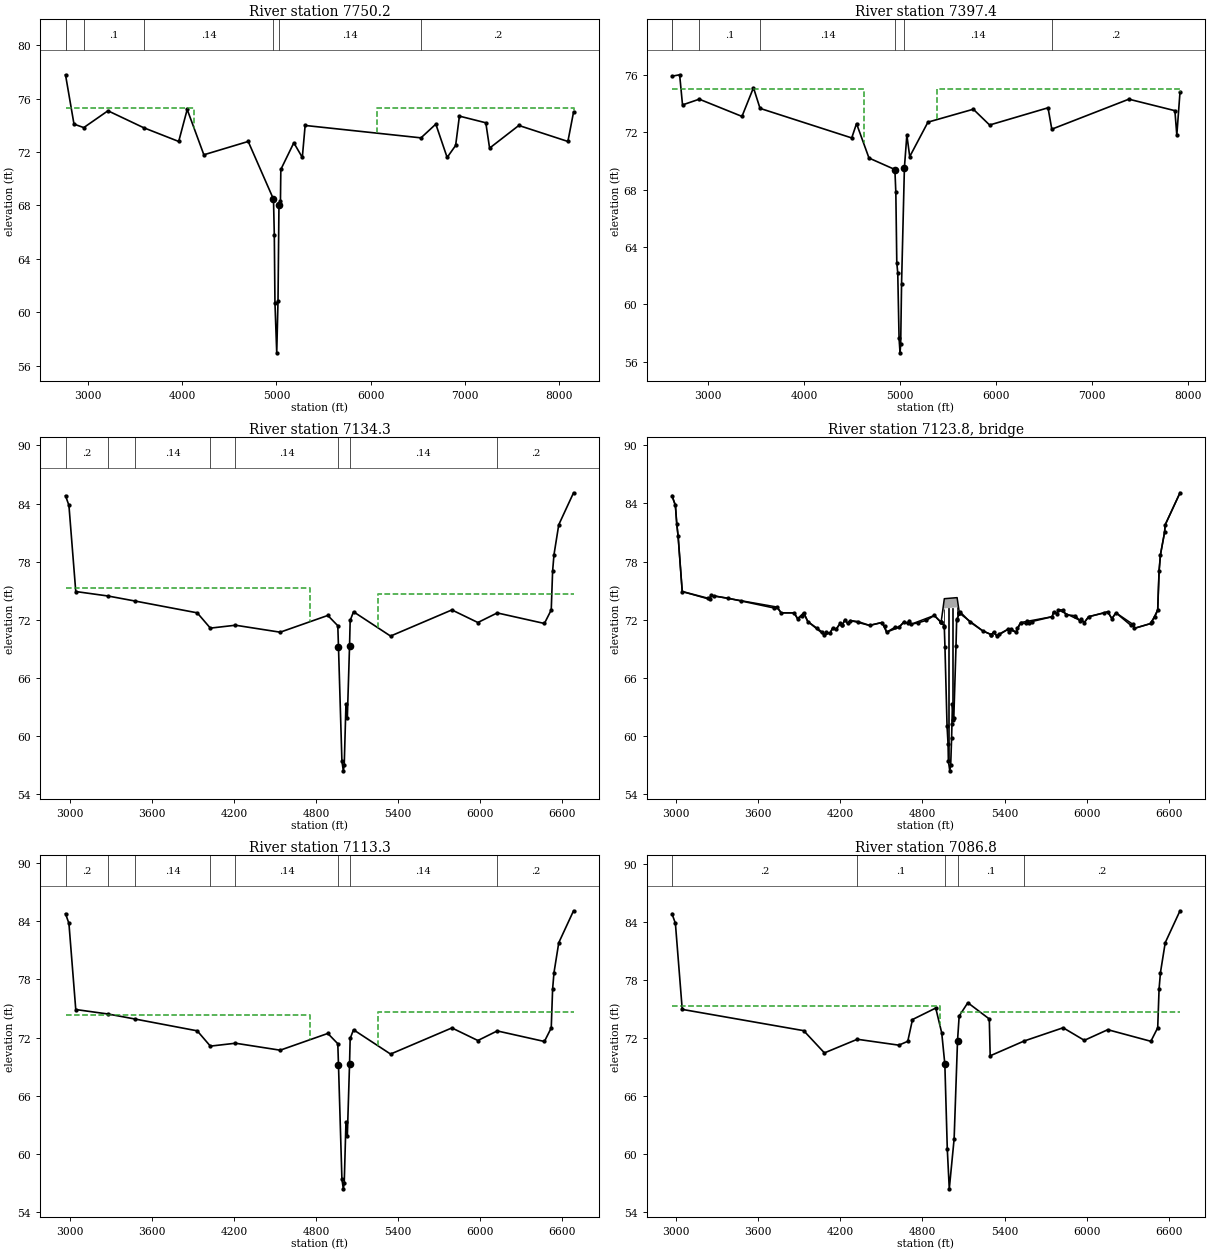
Type RM Length L Ch R = 1 ,7750.2  ,347.8,352.8,337
BEGIN DESCRIPTION:
Cross Section  7750.2
END DESCRIPTION:
XS GIS Cut Line= 6
      3143198.44     13917065.69      3143155.21     13915639.63
       3143130.1     13915024.25      3143029.63     13914691.44
      3142665.42     13914006.99      3141200.23     13912339.14
#Sta/Elev= 30
  2764.4    77.8  2854.4    74.1  2958.2   73.84  3214.4    75.1  3593.1   73.83
  3964.4    72.8  4054.4    75.2  4231.1    71.8  4701.1    72.8  4969.2   68.47
  4977.8   65.82  4984.7   60.71  5003.6   56.95  5017.1   60.85  5027.2   68.03
    5043   68.35    5047    70.7  5184.7    72.7  5274.7    71.6  5304.7      74
  6532.7   73.07    6690    74.1    6810    71.6    6900    72.5    6940    74.7
    7220    74.2    7260    72.3    7570      74    8090    72.8    8150      75
#Mann= 7 , 1 , 0
  2764.4      .2       0  2764.4     .14       0  2958.2      .1       0
  3593.1     .14       0  4969.2    .045       0  5027.2     .14       0
  6532.7      .2       0
#XS Ineff= 2 , 0
       0    4131    75.3    6070       0    75.3
Permanent Ineff=
       F       F
Bank Sta=4969.2,5027.2
XS Rating Curve= 0
Exp/Cntr=.3,.1

Type RM Length L Ch R = 1 ,7397.4  ,310.8,263.1,259.2
BEGIN DESCRIPTION:
Cross Section  7397.4 - Interpolated
END DESCRIPTION:
XS GIS Cut Line= 6
      3143549.99     13917178.69      3143610.56     13915985.57
      3143428.48     13914824.79      3142904.99     13913777.81
      3142097.55     13912926.94      3141928.92     13912368.39
#Sta/Elev= 30
    2621    75.9    2701      76    2731    73.9  2905.6    74.3    3351    73.1
    3471    75.1  3539.4   73.66  4495.7    71.6  4545.7    72.6  4675.7    70.2
  4945.7    69.4  4955.7    67.8  4965.7    62.9  4975.7    62.2 4989.31   57.65
 4999.61   56.63 5006.31   57.25 5015.41   61.44 5045.11   69.53  5070.6    71.8
  5100.6    70.3  5290.6    72.7  5763.7    73.6  5933.7    72.5    6543    73.7
  6582.2   72.21    7386    74.3    7866    73.5    7886    71.8  7919.4    74.8
#Mann= 7 , 1 , 0
    2621      .2       0    2621     .14       0  2905.6      .1       0
  3539.4     .14       0  4945.7    .045       0 5045.11     .14       0
  6582.2      .2       0
#XS Ineff= 2 , 0
       0    4619      75    5390       0      75
Permanent Ineff=
       F       F
Bank Sta=4945.7,5045.11
XS Rating Curve= 0
Exp/Cntr=.5,.3

Type RM Length L Ch R = 1 ,7134.3  ,21,21,21
BEGIN DESCRIPTION:
Upstream Section of Bridge/Culvert/Weir
END DESCRIPTION:
XS GIS Cut Line= 6
      3144108.08     13916796.79      3143740.46     13915184.59
      3143531.48     13914629.99      3143439.05     13914372.79
      3143183.56     13913918.23      3142713.78     13913435.62
#Sta/Elev= 30
  2968.4   84.81  2993.4   83.81  3043.4   74.91  3278.2   74.45  3476.3   73.93
  3931.5   72.71  4027.4   71.13  4211.2   71.43    4538   70.71 4886.21   72.44
 4959.21   71.38 4964.21   69.23 4989.31   57.41 4999.61   56.39 5006.31   57.01
 5018.91   63.31 5029.01   61.88 5045.11   69.29 5049.71   71.92 5074.21   72.82
    5345   70.31  5793.3   73.01  5983.3   71.71  6124.9    72.7  6469.8   71.61
  6519.8   73.01  6529.8   77.01  6539.8   78.71  6574.8   81.81  6682.9   85.11
#Mann= 8 , 1 , 0
  2968.4      .2       0  3278.2      .1       0  3476.3     .14       0
  4027.4      .1       0  4211.2     .14       0 4964.21    .045       0
 5045.11     .14       0  6124.9      .2       0
#XS Ineff= 2 , 0
       0    4755   75.31    5254       0   74.68
Permanent Ineff=
       F       F
Bank Sta=4964.21,5045.11
XS Rating Curve= 0
Exp/Cntr=.5,.3

Type RM Length L Ch R = 3 ,7123.8  ,,,
BEGIN DESCRIPTION:
12" PIPELINE U/S OF 59 FRONTAGE ROAD
END DESCRIPTION:
Bridge Culvert--1,0,-1,-1, 0
Deck Dist Width WeirC Skew NumUp NumDn MinLoCord MaxHiCord MaxSubmerge Is_Ogee
10,1,2.6,0, 60, 60, , , .95, 0, 1,1,,
  2968.4  2993.4  3003.4  3013.4  3043.4  3243.4  3253.4  3736.5  3766.5  3861.5
  3886.5  3931.5  3961.5    4083    4123    4143    4168    4198    4213    4233
    4253    4273    4413    4503    4538  4627.4  4667.4  4692.4  4702.4 4715.81
 4886.21 4936.11 4959.61 5053.11  5069.9 5240.31 5304.21    5320    5345    5425
    5485  5518.3  5748.3  5758.3  5783.3  5793.3  5983.3  6014.8  6154.8  6184.8
  6214.8  6339.8  6349.8  6469.8  6519.8  6529.8  6539.8  6569.8  6574.8  6682.9
    84.8    83.8    81.9    80.6    74.9    74.1    74.5    73.3    72.7    72.7
    72.1    72.7    71.8    70.4    70.6    71.1      71    71.6    71.4      72
    71.6    71.9    71.4    71.7    70.7    71.2    71.8    71.6    71.9   71.52
   72.43   71.72   74.16   74.27   72.66   70.84   70.44    70.7    70.3      71
    70.7    71.7    72.3    72.8    72.6      73    71.7    72.3    72.8    72.1
    72.7    71.5    71.1    71.6      73      77    78.7      81    81.8    85.1
    84.8    83.8    81.9    80.6    74.9    74.1    74.5    73.3    72.7    72.7
    72.1    72.7    71.8    70.4    70.6    71.1      71    71.6    71.4      72
    71.6    71.9    71.4    71.7    70.7    71.2    71.8    71.6    71.9   71.52
   72.43   71.71   73.16   73.27   72.65   70.84   70.44    70.7    70.3      71
    70.7    71.7    72.3    72.8    72.6      73    71.7    72.3    72.8    72.1
    72.7    71.5    71.1    71.6      73      77    78.7      81    81.8    85.1
  2968.4  2993.4  3003.4  3013.4  3043.4  3243.4  3253.4  3736.5  3766.5  3861.5
  3886.5  3931.5  3961.5    4083    4123    4143    4168    4198    4213    4233
    4253    4273    4413    4503    4538  4627.4  4667.4  4692.4  4702.4 4715.81
 4886.21 4936.11 4959.61 5053.11  5069.9 5240.31 5304.21    5320    5345    5425
    5485  5518.3  5748.3  5758.3  5783.3  5793.3  5983.3  6014.8  6154.8  6184.8
  6214.8  6339.8  6349.8  6469.8  6519.8  6529.8  6539.8  6569.8  6574.8  6682.9
    84.8    83.8    81.9    80.6    74.9    74.1    74.5    73.3    72.7    72.7
    72.1    72.7    71.8    70.4    70.6    71.1      71    71.6    71.4      72
    71.6    71.9    71.4    71.7    70.7    71.2    71.8    71.6    71.9   71.52
   72.43   71.72   74.16   74.27   72.66   70.84   70.44    70.7    70.3      71
    70.7    71.7    72.3    72.8    72.6      73    71.7    72.3    72.8    72.1
    72.7    71.5    71.1    71.6      73      77    78.7      81    81.8    85.1
    84.8    83.8    81.9    80.6    74.9    74.1    74.5    73.3    72.7    72.7
    72.1    72.7    71.8    70.4    70.6    71.1      71    71.6    71.4      72
    71.6    71.9    71.4    71.7    70.7    71.2    71.8    71.6    71.9   71.52
   72.43   71.71   73.16   73.27   72.65   70.84   70.44    70.7    70.3      71
    70.7    71.7    72.3    72.8    72.6      73    71.7    72.3    72.8    72.1
    72.7    71.5    71.1    71.6      73      77    78.7      81    81.8    85.1
Pier Skew, UpSta & Num, DnSta & Num=  ,4959.2, 2 ,4959.2, 2 , 0 , 0 , 0 ,,
     1.4     1.4
   70.07   74.16
     1.4     1.4
   70.07   74.16
Pier Skew, UpSta & Num, DnSta & Num=  ,4989.7, 2 ,4989.7, 2 , 0 , 0 , 0 ,,
     1.4     1.4
   56.29   74.19
     1.4     1.4
   56.29   74.19
Pier Skew, UpSta & Num, DnSta & Num=  ,5018.9, 2 ,5018.9, 2 , 0 , 0 , 0 ,,
     1.4     1.4
   61.88   74.23
     1.4     1.4
   61.88   74.23
Pier Skew, UpSta & Num, DnSta & Num=  ,5049.7, 2 ,5049.7, 2 , 0 , 0 , 0 ,,
     1.4     1.4
   70.51   74.27
     1.4     1.4
   70.51   74.27
BR Coef= 1 , 1 , 0 ,1.25, 0 ,,,.8,0,2,0,
WSPro=,,,, 1 ,,,, 0 ,,,, 0 ,,,,-1 ,-1 ,-1 , 0 , 0 , 0 , 0 , 0
BR U #Sta/Elev= 113
  2968.4    84.8  2993.4    83.8  3003.4    81.9  3013.4    80.6  3043.4    74.9
  3233.4    74.2  3243.4    74.1  3253.4    74.5  3278.2   74.44  3381.1    74.2
  3476.3   73.92  3716.1    73.2  3736.5    73.3  3766.5    72.7  3861.5    72.7
  3886.5    72.1  3921.5    72.4  3931.5    72.7  3961.5    71.8  4027.4   71.12
    4068    70.7    4083    70.4    4093    70.7    4123    70.6    4143    71.1
    4168      71    4198    71.6  4211.2   71.42    4213    71.4    4233      72
    4253    71.6    4273    71.9    4328    71.8    4413    71.4    4503    71.7
    4523    71.3    4538    70.7    4598    71.2  4627.4    71.2  4667.4    71.8
  4692.4    71.6  4702.4    71.9 4715.81   71.52 4764.01   71.66 4827.61   71.92
 4886.21   72.43 4935.91   71.71 4936.02   71.71 4936.11   71.71 4959.21   71.37
 4959.61    71.2 4964.21   69.22 4979.61   61.01 4987.01   59.16 4989.31    57.4
 4999.61   56.38 5006.31      57 5012.91   59.78 5015.41   61.19 5018.91    63.3
 5026.31   61.67 5029.01   61.87 5045.11   69.28 5049.71   71.91 5053.11   72.03
  5069.9   72.65 5070.01   72.66 5070.11   72.66 5074.21   72.81 5148.51   71.74
 5240.31   70.84 5304.21   70.44 5304.31   70.44    5320    70.7    5345    70.3
    5360    70.5    5425      71    5435    70.7    5450      71    5485    70.7
  5493.3    71.1  5518.3    71.7  5553.3    71.6  5563.3    71.9  5578.3    71.6
  5598.3    71.8  5748.3    72.3  5758.3    72.8  5783.3    72.6  5793.3      73
  5828.3      73  5848.3    72.5  5918.3    72.4  5948.3    71.9  5958.3    72.1
  5983.3    71.7  6014.8    72.3  6124.9   72.69  6154.8    72.8  6184.8    72.1
  6214.8    72.7  6324.8    71.4  6339.8    71.5  6349.8    71.1  6469.8    71.6
  6474.8    71.8  6499.8    72.3  6519.8      73  6529.8      77  6539.8    78.7
  6569.8      81  6574.8    81.8  6682.9    85.1
BR U #Mann= 8
  2968.4      .2  3278.2      .1  3476.3     .14  4027.4      .1  4211.2     .14
 4964.21    .045 5045.11     .14  6124.9      .2
BR U Banks=4964.21,5045.11
BR D #Sta/Elev= 113
  2968.4    84.8  2993.4    83.8  3003.4    81.9  3013.4    80.6  3043.4    74.9
  3233.4    74.2  3243.4    74.1  3253.4    74.5  3278.2   74.44  3381.1    74.2
  3476.3   73.92  3716.1    73.2  3736.5    73.3  3766.5    72.7  3861.5    72.7
  3886.5    72.1  3921.5    72.4  3931.5    72.7  3961.5    71.8  4027.4   71.12
    4068    70.7    4083    70.4    4093    70.7    4123    70.6    4143    71.1
    4168      71    4198    71.6  4211.2   71.42    4213    71.4    4233      72
    4253    71.6    4273    71.9    4328    71.8    4413    71.4    4503    71.7
    4523    71.3    4538    70.7    4598    71.2  4627.4    71.2  4667.4    71.8
  4692.4    71.6  4702.4    71.9 4715.81   71.52 4764.01   71.66 4827.61   71.92
 4886.21   72.43 4935.91   71.71 4936.02   71.71 4936.11   71.71 4959.21   71.37
 4959.61    71.2 4964.21   69.22 4979.61   61.01 4987.01   59.16 4989.31    57.4
 4999.61   56.38 5006.31      57 5012.91   59.78 5015.41   61.19 5018.91    63.3
 5026.31   61.67 5029.01   61.87 5045.11   69.28 5049.71   71.91 5053.11   72.03
  5069.9   72.65 5070.01   72.66 5070.11   72.66 5074.21   72.81 5148.51   71.74
 5240.31   70.84 5304.21   70.44 5304.31   70.44    5320    70.7    5345    70.3
    5360    70.5    5425      71    5435    70.7    5450      71    5485    70.7
  5493.3    71.1  5518.3    71.7  5553.3    71.6  5563.3    71.9  5578.3    71.6
  5598.3    71.8  5748.3    72.3  5758.3    72.8  5783.3    72.6  5793.3      73
  5828.3      73  5848.3    72.5  5918.3    72.4  5948.3    71.9  5958.3    72.1
  5983.3    71.7  6014.8    72.3  6124.9   72.69  6154.8    72.8  6184.8    72.1
  6214.8    72.7  6324.8    71.4  6339.8    71.5  6349.8    71.1  6469.8    71.6
  6474.8    71.8  6499.8    72.3  6519.8      73  6529.8      77  6539.8    78.7
  6569.8      81  6574.8    81.8  6682.9    85.1
BR D #Mann= 8
  2968.4      .2  3278.2      .1  3476.3     .14  4027.4      .1  4211.2     .14
 4964.21    .045 5045.11     .14  6124.9      .2
BR D Banks=4964.21,5045.11
BC Design=,, 0 ,, 0 ,,,,,,

Type RM Length L Ch R = 1 ,7113.3  ,26.5,26.5,26.5
BEGIN DESCRIPTION:
Downstream Section of Bridge/Culvert/Weir
END DESCRIPTION:
XS GIS Cut Line= 6
      3144129.07     13916796.33      3143761.46     13915184.13
      3143552.48     13914629.53      3143460.05     13914372.33
      3143204.56     13913917.77      3142734.77     13913435.16
#Sta/Elev= 30
  2968.4   84.79  2993.4   83.79  3043.4   74.89  3278.2   74.43  3476.3   73.91
  3931.5   72.69  4027.4   71.11  4211.2   71.41    4538   70.69 4886.21   72.42
 4959.21   71.36 4964.21   69.21 4989.31   57.39 4999.61   56.37 5006.31   56.99
 5018.91   63.29 5029.01   61.86 5045.11   69.27 5049.71    71.9 5074.21    72.8
    5345   70.29  5793.3   72.99  5983.3   71.69  6124.9   72.68  6469.8   71.59
  6519.8   72.99  6529.8   76.99  6539.8   78.69  6574.8   81.79  6682.9   85.09
#Mann= 8 , 1 , 0
  2968.4      .2       0  3278.2      .1       0  3476.3     .14       0
  4027.4      .1       0  4211.2     .14       0 4964.21    .045       0
 5045.11     .14       0  6124.9      .2       0
#XS Ineff= 2 , 0
       0    4755   74.31    5254       0   74.68
Permanent Ineff=
       F       F
Bank Sta=4964.21,5045.11
XS Rating Curve= 0
Exp/Cntr=.5,.3

Type RM Length L Ch R = 1 ,7086.8  ,420,420,420
BEGIN DESCRIPTION:
Upstream Section of Bridge/Culvert/Weir
END DESCRIPTION:
XS GIS Cut Line= 5
      3144324.35     13916718.57       3143913.3     13915346.94
      3143715.18      13914794.2      3143553.76     13914343.83
      3143147.72     13913196.56
#Sta/Elev= 30
  2968.4   84.81  2993.4   83.81  3043.4   74.91  3931.5   72.71    4083   70.41
  4323.4   71.82  4627.4   71.21  4692.4   71.61  4726.9   73.86  4896.9   75.05
  4940.8   72.47  4963.5   69.24  4981.5   60.43  4995.9   56.35  5031.3   61.51
  5056.2   71.68  5068.2   74.22  5131.4    75.6  5288.4   73.92    5295   70.11
  5543.1   71.64  5828.3   73.01  5983.3   71.71  6154.8   72.81  6469.8   71.61
  6519.8   73.01  6529.8   77.01  6539.8   78.71  6574.8   81.81  6682.9   85.11
#Mann= 5 , 1 , 0
  2968.4      .2       0  4323.4      .1       0  4963.5    .045       0
  5056.2      .1       0  5543.1      .2       0
#XS Ineff= 2 , 0
       0    4928   75.31    5078       0   74.68
Permanent Ineff=
       F       F
Bank Sta=4963.5,5056.2
XS Rating Curve= 0
Exp/Cntr=.5,.3

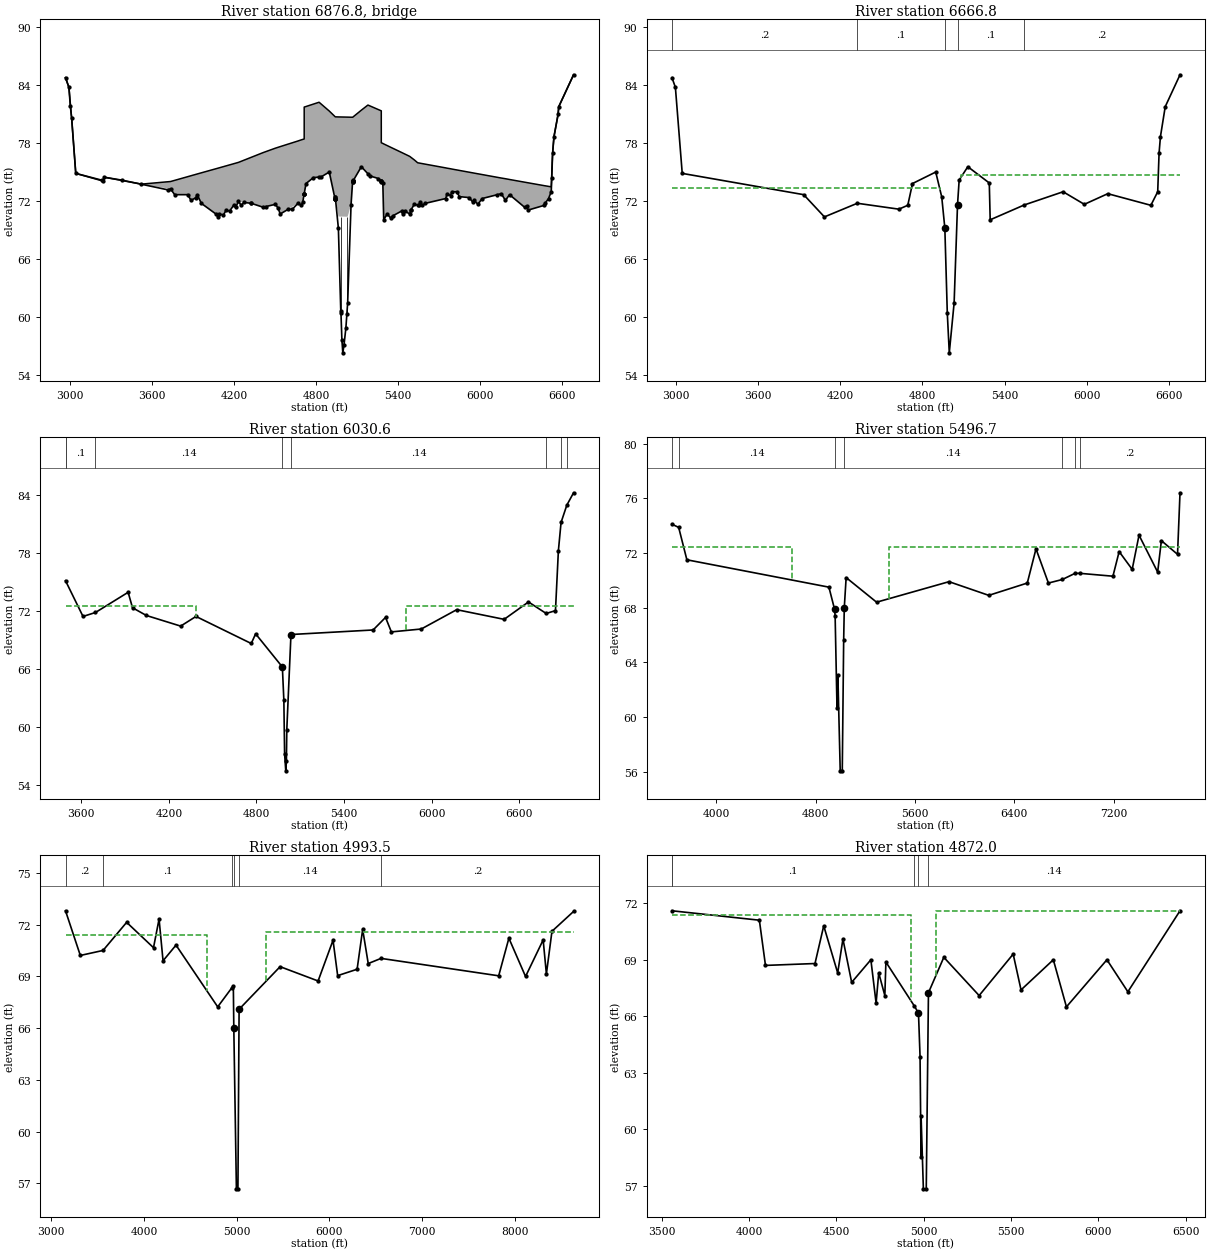
Type RM Length L Ch R = 3 ,6876.8  ,,,
BEGIN DESCRIPTION:
COMBINED STRUCTURE - 59 FREEWAY AND FRONTAGE ROADS
Structure ID: P35-03
END DESCRIPTION:
Bridge Culvert--1,0,-1,-1, 0
Deck Dist Width WeirC Skew NumUp NumDn MinLoCord MaxHiCord MaxSubmerge Is_Ogee
10,400,2.6,0, 60, 60, , , .95, 0, 1,1,,
  2968.4  2993.4  3013.4  3043.4  3243.4  3253.4  3523.4  3736.5  3766.5  3861.5
  3886.5  3931.5  3961.5    4083    4213    4233    4413    4503    4538  4667.4
  4692.4 4713.49  4713.6  4726.9  4822.4  4896.9  4940.8  4963.5  5031.3  5056.2
  5068.2  5131.4  5179.5  5277.2 5277.31  5288.4    5295    5320    5345    5425
    5485  5518.3  5543.1  5748.3  5758.3  5783.3  5793.3  5983.3  6014.8  6154.8
  6184.8  6214.8  6349.8  6469.8  6519.8  6529.8  6539.8  6569.8  6574.8  6682.9
    84.8    83.8    80.6    74.9    74.1    74.5   73.79   74.06   74.18   74.56
   74.66   74.84   74.96   75.44   75.96   76.04   77.05   77.51   77.67   78.25
   78.37   78.46   81.76   81.82   82.26   81.35   80.75   80.74   80.72   80.71
   80.71   81.44   81.97   81.37   78.07      78   77.95   77.78   77.61   77.07
   76.66    76.3      76   75.47   75.44   75.38   75.35   74.86   74.78   74.42
   74.35   74.27   73.93   73.63   73.51      77    78.7      81    81.8    85.1
    84.8    83.8    80.6    74.9    74.1    74.5   73.78    73.3    72.7    72.7
    72.1    72.7    71.8    70.4    71.4      72    71.4    71.7    70.7    71.8
    71.6   72.78   72.79   73.85   74.52   75.04   72.46   70.44   70.42   71.67
   74.21   75.59   74.86   74.07   74.07   73.91    70.1    70.7    70.3      71
    70.7    71.7   71.63    72.3    72.8    72.6      73    71.7    72.3    72.8
    72.1    72.7    71.1    71.6      73      77    78.7      81    81.8    85.1
  2968.4  2993.4  3013.4  3043.4  3243.4  3253.4  3523.4  3736.5  3766.5  3861.5
  3886.5  3931.5  3961.5    4083    4213    4233    4413    4503    4538  4667.4
  4692.4 4713.49  4713.6  4726.9  4822.4  4896.9  4940.8  4963.5  5031.3  5056.2
  5068.2  5131.4  5179.5  5277.2 5277.31  5288.4    5295    5320    5345    5425
    5485  5518.3  5543.1  5748.3  5758.3  5783.3  5793.3  5983.3  6014.8  6154.8
  6184.8  6214.8  6349.8  6469.8  6519.8  6529.8  6539.8  6569.8  6574.8  6682.9
    84.8    83.8    80.6    74.9    74.1    74.5   73.79   74.06   74.18   74.56
   74.66   74.84   74.96   75.44   75.96   76.04   77.05   77.51   77.67   78.25
   78.37   78.46   81.76   81.82   82.26   81.35   80.75   80.74   80.72   80.71
   80.71   81.44   81.97   81.37   78.07      78   77.95   77.78   77.61   77.07
   76.66    76.3      76   75.47   75.44   75.38   75.35   74.86   74.78   74.42
   74.35   74.27   73.93   73.63   73.51      77    78.7      81    81.8    85.1
   84.74   83.74   80.54   74.84   74.04   74.44   73.72   73.24   72.64   72.64
   72.04   72.64   71.74   70.34   71.34   71.94   71.34   71.64   70.64   71.74
   71.54   72.72   72.73   73.79   74.46   74.98    72.4   70.38   70.36   71.61
   74.15   75.53    74.8   74.01   74.01   73.85   70.04   70.64   70.24   70.94
   70.64   71.64   71.57   72.24   72.74   72.54   72.94   71.64   72.24   72.74
   72.04   72.64   71.04   71.54   72.94   76.94   78.64   80.94   81.74   85.04
Pier Skew, UpSta & Num, DnSta & Num=  ,4981.9, 2 ,4981.9, 2 , 0 , 0 , 0 ,,
     1.4     1.4
   59.37   71.44
     1.4     1.4
   59.31   71.38
Pier Skew, UpSta & Num, DnSta & Num=  ,5025.8, 2 ,5025.8, 2 , 0 , 0 , 0 ,,
     1.4     1.4
   59.26   71.42
     1.4     1.4
    59.2   71.36
Abutment Skew #Up #Dn= , 2 , 2
  4939.2  4940.8
   72.24   72.46
  4939.2  4940.8
   72.18    72.4
BR Coef= 1 , 1 , 0 ,1.25, 0 ,,,.8,0,2,0,
WSPro=,,,, 1 ,,,, 0 ,,,, 0 ,,,,-1 ,-1 ,-1 , 0 , 0 , 0 , 0 , 0
BR U #Sta/Elev= 127
  2968.4    84.8  2993.4    83.8  3003.4    81.9  3013.4    80.6  3043.4    74.9
  3233.4    74.2  3243.4    74.1  3253.4    74.5  3381.1    74.2  3523.4   73.78
  3716.1    73.2  3736.5    73.3  3766.5    72.7  3861.5    72.7  3886.5    72.1
  3921.5    72.4  3931.5    72.7  3961.5    71.8    4068    70.7    4083    70.4
    4093    70.7    4123    70.6    4143    71.1    4168      71    4198    71.6
    4213    71.4    4233      72    4253    71.6    4273    71.9  4323.4   71.81
    4328    71.8    4413    71.4  4433.4   71.47    4503    71.7    4523    71.3
    4538    70.7    4598    71.2  4627.4    71.2  4667.4    71.8  4692.4    71.6
  4702.4    71.9  4713.1   72.75 4713.49   72.78  4713.6   72.79 4713.71    72.8
  4726.9   73.85  4780.5   74.46  4822.4   74.52  4837.1   74.54  4896.9   75.04
  4939.1   72.26  4939.2   72.25 4939.31   72.25  4939.4   72.24  4939.7   72.22
  4940.7   72.44  4940.8   72.46  4963.5   69.23  4981.5   60.42  4981.9   60.66
  4989.1   57.71  4995.9   56.34  5004.7   57.16  5018.5   58.94  5025.8    60.4
  5031.3    61.5  5056.2   71.67  5068.2   74.21  5068.3   74.06  5068.4   74.06
  5068.7   74.07 5068.79   74.07  5068.9   74.07  5069.1   74.08  5131.4   75.59
  5179.5   74.86  5194.3   74.64    5256   74.37 5277.09   74.07  5277.2   74.07
 5277.31   74.07  5277.5   74.06  5288.4   73.91    5295    70.1    5320    70.7
    5345    70.3    5360    70.5    5425      71    5435    70.7    5450      71
    5485    70.7  5493.3    71.1  5493.4    71.1  5518.3    71.7  5543.1   71.63
  5553.3    71.6  5563.3    71.9  5578.3    71.6  5598.3    71.8  5748.3    72.3
  5758.3    72.8  5783.3    72.6  5793.3      73  5828.3      73  5848.3    72.5
  5918.3    72.4  5948.3    71.9  5958.3    72.1  5983.3    71.7  6014.8    72.3
  6123.4   72.69  6154.8    72.8  6184.8    72.1  6214.8    72.7  6324.8    71.4
  6339.8    71.5  6349.8    71.1  6469.8    71.6  6474.8    71.8  6499.8    72.3
  6519.8      73  6523.4   74.44  6529.8      77  6539.8    78.7  6569.8      81
  6574.8    81.8  6682.9    85.1
BR U #Mann= 5
  2968.4      .2  4323.4      .1  4963.5    .045  5056.2      .1  5543.1      .2
BR U Banks=4963.5,5056.2
BR D #Sta/Elev= 127
  2968.4   84.74  2993.4   83.74  3003.4   81.84  3013.4   80.54  3043.4   74.84
  3233.4   74.14  3243.4   74.04  3253.4   74.44  3381.1   74.14  3523.4   73.72
  3716.1   73.14  3736.5   73.24  3766.5   72.64  3861.5   72.64  3886.5   72.04
  3921.5   72.34  3931.5   72.64  3961.5   71.74    4068   70.64    4083   70.34
    4093   70.64    4123   70.54    4143   71.04    4168   70.94    4198   71.54
    4213   71.34    4233   71.94    4253   71.54    4273   71.84  4323.4   71.75
    4328   71.74    4413   71.34  4433.4   71.41    4503   71.64    4523   71.24
    4538   70.64    4598   71.14  4627.4   71.14  4667.4   71.74  4692.4   71.54
  4702.4   71.84  4713.1   72.69 4713.49   72.72  4713.6   72.73 4713.71   72.74
  4726.9   73.79  4780.5    74.4  4822.4   74.46  4837.1   74.48  4896.9   74.98
  4939.1    72.2  4939.2   72.19 4939.31   72.19  4939.4   72.18  4939.7   72.16
  4940.7   72.38  4940.8    72.4  4963.5   69.17  4981.5   60.36  4981.9    60.6
  4989.1   57.65  4995.9   56.28  5004.7    57.1  5018.5   58.88  5025.8   60.34
  5031.3   61.44  5056.2   71.61  5068.2   74.15  5068.3      74  5068.4      74
  5068.7   74.01 5068.79   74.01  5068.9   74.01  5069.1   74.02  5131.4   75.53
  5179.5    74.8  5194.3   74.58    5256   74.31 5277.09   74.01  5277.2   74.01
 5277.31   74.01  5277.5      74  5288.4   73.85    5295   70.04    5320   70.64
    5345   70.24    5360   70.44    5425   70.94    5435   70.64    5450   70.94
    5485   70.64  5493.3   71.04  5493.4   71.04  5518.3   71.64  5543.1   71.57
  5553.3   71.54  5563.3   71.84  5578.3   71.54  5598.3   71.74  5748.3   72.24
  5758.3   72.74  5783.3   72.54  5793.3   72.94  5828.3   72.94  5848.3   72.44
  5918.3   72.34  5948.3   71.84  5958.3   72.04  5983.3   71.64  6014.8   72.24
  6123.4   72.63  6154.8   72.74  6184.8   72.04  6214.8   72.64  6324.8   71.34
  6339.8   71.44  6349.8   71.04  6469.8   71.54  6474.8   71.74  6499.8   72.24
  6519.8   72.94  6523.4   74.38  6529.8   76.94  6539.8   78.64  6569.8   80.94
  6574.8   81.74  6682.9   85.04
BR D #Mann= 5
  2968.4      .2  4323.4      .1  4963.5    .045  5056.2      .1  5543.1      .2
BR D Banks=4963.5,5056.2
BC Design=,, 0 ,, 0 ,,,,,,

Type RM Length L Ch R = 1 ,6666.8  ,636.2,636.2,636.2
BEGIN DESCRIPTION:
Downstream Section of Bridge/Culvert/Weir
END DESCRIPTION:
XS GIS Cut Line= 5
      3144735.52     13916632.92      3144324.48     13915261.28
      3144126.36     13914708.54      3143964.94     13914258.17
      3143558.89     13913110.91
#Sta/Elev= 30
  2968.4   84.73  2993.4   83.73  3043.4   74.83  3931.5   72.63    4083   70.33
  4323.4   71.74  4627.4   71.13  4692.4   71.53  4726.9   73.78  4896.9   74.97
  4940.8   72.39  4963.5   69.16  4981.5   60.35  4995.9   56.27  5031.3   61.43
  5056.2    71.6  5068.2   74.14  5131.4   75.52  5288.4   73.84    5295   70.03
  5543.1   71.56  5828.3   72.93  5983.3   71.63  6154.8   72.73  6469.8   71.53
  6519.8   72.93  6529.8   76.93  6539.8   78.63  6574.8   81.73  6682.9   85.03
#Mann= 5 , 1 , 0
  2968.4      .2       0  4323.4      .1       0  4963.5    .045       0
  5056.2      .1       0  5543.1      .2       0
#XS Ineff= 2 , 0
       0    4928   73.31    5078       0   74.68
Permanent Ineff=
       F       F
Bank Sta=4963.5,5056.2
XS Rating Curve= 0
Exp/Cntr=.5,.3

Type RM Length L Ch R = 1 ,6030.6  ,564.7,533.9,453.8
BEGIN DESCRIPTION:
Cross Section  6030.6
END DESCRIPTION:
XS GIS Cut Line= 6
      3144681.22     13916044.53      3144577.56     13915664.24
      3144707.56     13914340.61      3144648.47     13914110.16
      3143738.48     13913347.89      3143556.41     13913079.92
#Sta/Elev= 30
  3491.7    75.1  3611.7    71.4  3697.1   71.81  3920.9    73.9  3950.9    72.3
  4045.9    71.5  4280.9    70.4  4385.9    71.4  4764.6    68.6  4794.6    69.6
  4977.9   66.17  4988.1   62.71  4993.2   57.17  5001.2   55.42  5005.6   56.45
  5008.3   59.69  5036.8   69.53  5599.9      70  5684.9    71.3  5724.9    69.8
  5929.9    70.1  6172.7    72.1  6497.7    71.1  6664.5    72.9  6785.8   71.71
  6849.5      72  6869.5    78.2  6887.8   81.13  6927.4   82.92  6973.4    84.2
#Mann= 8 , 1 , 0
  3491.7      .2       0  3491.7      .1       0  3697.1     .14       0
  4977.9    .045       0  5036.8     .14       0  6785.8      .1       0
  6887.8     .14       0  6927.4      .2       0
#XS Ineff= 2 , 0
       0    4385    72.5    5826       0    72.5
Permanent Ineff=
       F       F
Bank Sta=4977.9,5036.8
XS Rating Curve= 0
Exp/Cntr=.3,.1

Type RM Length L Ch R = 1 ,5496.7  ,539.8,503.2,480.3
BEGIN DESCRIPTION:
Cross Section  5496.7 - Interpolated
END DESCRIPTION:
XS GIS Cut Line= 6
      3145042.64     13915821.95      3145161.68     13915562.23
      3145252.72     13914961.35      3145025.12      13913741.4
      3144579.02     13912858.29      3143691.59      13912479.2
#Sta/Elev= 30
  3643.2    74.1  3697.1   73.87  3763.2    71.5  4906.6    69.5  4951.6    67.9
  4956.6    67.4  4971.6    60.7  4978.6   63.08  4997.6   56.07  5014.1   56.07
  5025.3    65.6  5030.3      68  5045.3    70.2  5290.3    68.4  5873.5    69.9
  6193.5    68.9  6503.5    69.8  6573.5    72.3  6673.5    69.8  6785.8   70.06
  6887.8   70.51  6927.4   70.51  7192.9    70.3  7242.9    72.1  7347.9    70.8
  7402.9    73.3  7552.9    70.6  7582.9    72.9  7712.9    71.9  7732.9    76.4
#Mann= 7 , 1 , 0
  3643.2      .1       0  3697.1     .14       0  4951.6    .045       0
  5030.3     .14       0  6785.8      .1       0  6887.8     .14       0
  6927.4      .2       0
#XS Ineff= 2 , 0
       0    4608    72.4    5389       0    72.4
Permanent Ineff=
       F       F
Bank Sta=4951.6,5030.3
XS Rating Curve= 0
Exp/Cntr=.3,.1

Type RM Length L Ch R = 1 ,4993.5  ,98.8,121.5,94.1
BEGIN DESCRIPTION:
Cross Section  4993.5 - Interpolated
END DESCRIPTION:
XS GIS Cut Line= 6
      3145985.74     13916067.25      3145786.88     13915033.16
      3145669.45     13914420.57      3145358.32     13913296.62
      3145240.62     13912858.76      3144531.19     13910788.84
#Sta/Elev= 30
  3152.7    72.8  3312.7   70.21  3557.8    70.5  3812.7   72.13  4102.7   70.66
  4162.7   72.32  4205.7    69.9  4345.7   70.81  4795.7   67.23  4946.2   68.32
  4964.5   68.43  4969.6   66.01  4997.6   56.68  5014.1   56.68  5026.7   67.09
  5469.5   69.56  5879.5   68.73  6040.7   71.09  6090.7   69.04  6300.7   69.41
  6360.7   71.72  6420.7   69.74  6558.7   70.04  7829.1   69.03  7939.1   71.21
  8119.1   68.99  8309.1   71.11  8344.1   69.14  8404.1   71.61  8637.2   72.76
#Mann= 6 , 1 , 0
  3152.7      .2       0  3557.8      .1       0  4946.2     .14       0
  4969.6    .045       0  5026.7     .14       0  6558.7      .2       0
#XS Ineff= 2 , 0
       0    4678   71.37    5319       0   71.57
Permanent Ineff=
       F       F
Bank Sta=4969.6,5026.7
XS Rating Curve= 0
Exp/Cntr=.5,.3

Type RM Length L Ch R = 1 ,4872.0  ,38,38,38
BEGIN DESCRIPTION:
Upstream Section of Bridge/Culvert/Weir
END DESCRIPTION:
XS GIS Cut Line= 4
      3146125.22     13915586.83      3145965.68     13915025.47
      3145741.14     13914251.39      3145339.77     13912785.31
#Sta/Elev= 30
  3557.8   71.59  4058.3   71.09  4093.3   68.69  4376.9   68.79  4426.9   70.79
  4506.9   68.29  4536.9   70.09  4586.9   67.79  4696.9   68.99  4726.9   66.69
  4741.9   68.29  4776.9   67.09    4783   68.87  4946.2   66.53  4969.6   66.16
  4978.6   63.84  4984.1   58.52  4984.5   60.68  4997.6   56.83  5014.1   56.83
  5026.7   67.24  5114.7   69.12  5316.9   67.09  5511.9   69.29  5556.9   67.39
  5741.9   68.99  5816.9   66.49  6048.8   68.99  6168.8   67.29  6467.4   71.59
#Mann= 5 , 1 , 0
  3557.8      .2       0  3557.8      .1       0  4946.2     .14       0
  4969.6    .045       0  5026.7     .14       0
#XS Ineff= 2 , 0
       0    4928   71.37    5069       0   71.57
Permanent Ineff=
       F       F
Bank Sta=4969.6,5026.7
XS Rating Curve= 0
Exp/Cntr=.5,.3