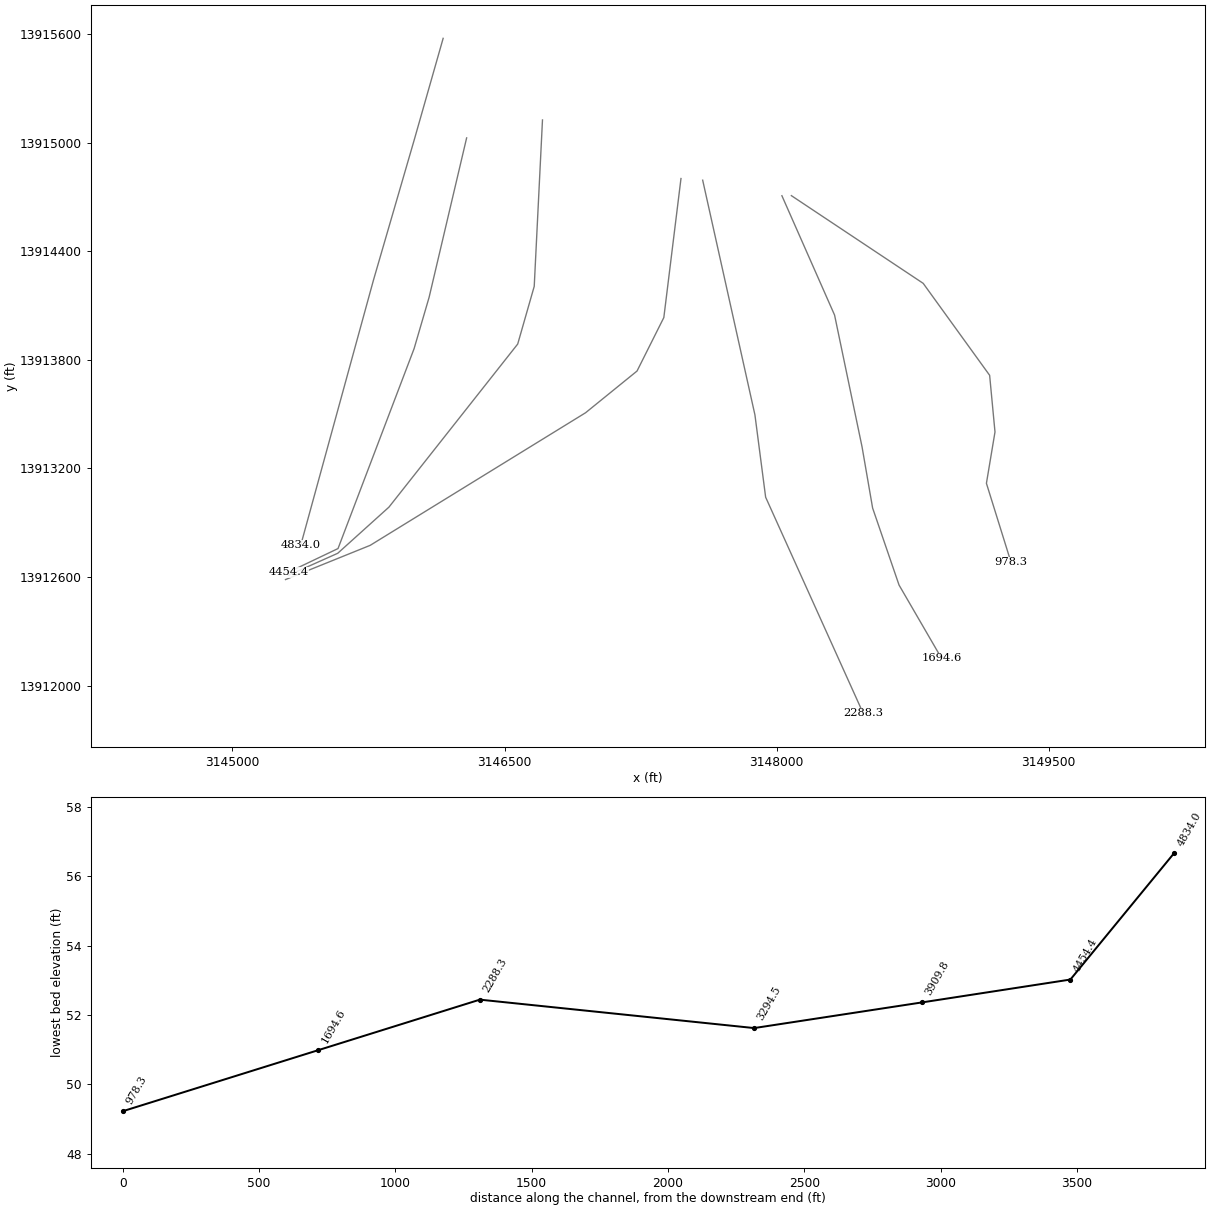
HEC-RAS study P130-05-00.PRJ: P130-05-00

--- P130-05-00.g01 (geometry) --- (continued)

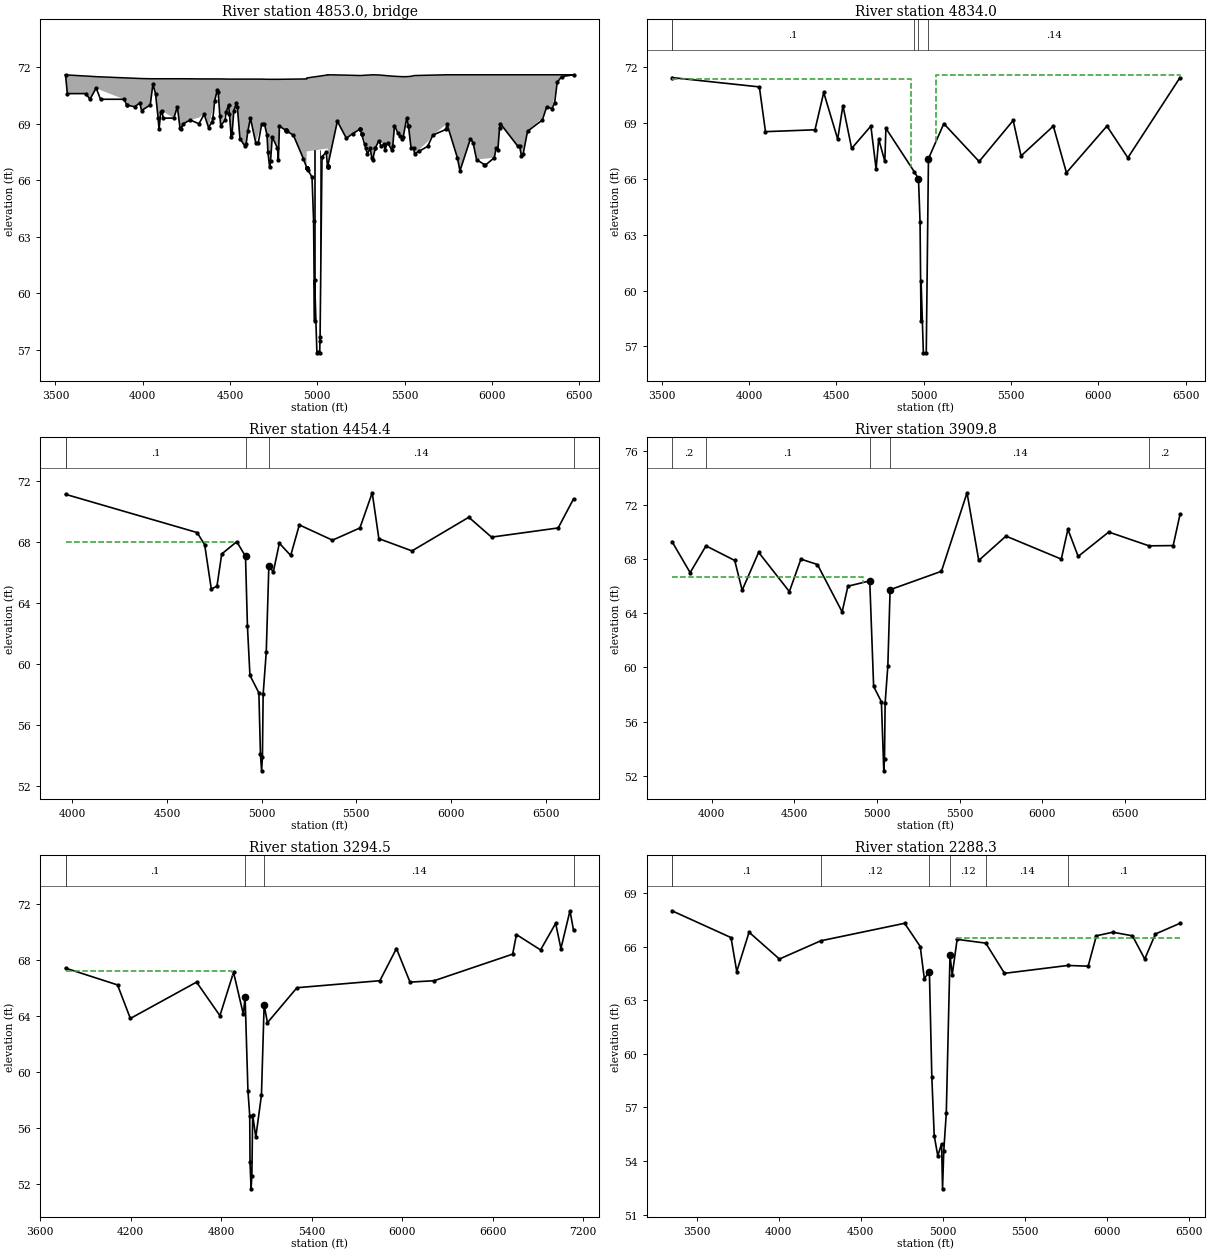
Type RM Length L Ch R = 3 ,4853.0  ,,,
BEGIN DESCRIPTION:
SOUTHERN PACIFIC RAILROAD
Structure ID: P35-01
END DESCRIPTION:
Bridge Culvert--1,0,-1,-1, 0
Deck Dist Width WeirC Skew NumUp NumDn MinLoCord MaxHiCord MaxSubmerge Is_Ogee
10,18,2.6,0, 60, 60, , , .95, 0, 1,1,,
  3557.8  3568.3  3698.3  3733.3  3993.3  4043.3  4058.3  4073.3  4093.3  4108.3
  4178.3  4198.3  4218.3  4351.9  4376.9  4426.9  4446.9  4491.9  4506.9  4521.9
  4536.9  4556.9  4586.9  4616.9  4646.9  4681.9  4711.9  4726.9  4741.9  4776.9
    4783    4863  4938.9  4939.2  5058.4 5059.39  5059.5  5114.7  5166.2  5245.4
  5316.9  5351.9  5426.9  5441.9  5486.9  5511.9  5536.9  5556.9  5741.9  5816.9
  5876.9  5911.9  6013.8  6033.8  6048.8  6168.8  6203.8  6343.8  6373.8  6467.4
    71.6   71.59   71.52    71.5    71.4   71.39   71.39   71.39   71.39   71.39
   71.39   71.39   71.39   71.38   71.38   71.38   71.38   71.37   71.37   71.37
   71.37   71.37   71.37   71.37   71.37   71.37   71.36   71.36   71.36   71.36
   71.36   71.37   71.38   71.43   71.59   71.59    71.6   71.59   71.58   71.56
    71.6   71.59   71.53   71.52    71.5    71.5   71.52   71.56    71.6    71.6
    71.6    71.6    71.6    71.6    71.6    71.6    71.6    71.6    71.6    71.6
    71.6    70.6    70.3    70.9    69.7      70    71.1    70.6    68.7    69.7
    69.3    69.9    68.7    69.5    68.8    70.8    68.9      70    68.3    69.7
    70.1    68.2    67.8    69.3      68      69    68.4    66.7    68.3    67.1
   68.88   68.39   66.67   67.53   67.69   67.69   66.74   69.13   68.23   68.72
    67.1    68.1    67.6    68.9    68.2    69.3    67.7    67.4      69    66.5
    68.2    67.1    67.2    67.6      69    67.3    68.6    69.8    71.2    71.6
  3557.8  3568.3  3698.3  3733.3  3993.3  4043.3  4058.3  4073.3  4093.3  4108.3
  4178.3  4198.3  4218.3  4351.9  4376.9  4426.9  4446.9  4491.9  4506.9  4521.9
  4536.9  4556.9  4586.9  4616.9  4646.9  4681.9  4711.9  4726.9  4741.9  4776.9
    4783    4863  4938.9  4939.2  5058.4 5059.39  5059.5  5114.7  5166.2  5245.4
  5316.9  5351.9  5426.9  5441.9  5486.9  5511.9  5536.9  5556.9  5741.9  5816.9
  5876.9  5911.9  6013.8  6033.8  6048.8  6168.8  6203.8  6343.8  6373.8  6467.4
    71.6   71.59   71.52    71.5    71.4   71.39   71.39   71.39   71.39   71.39
   71.39   71.39   71.39   71.38   71.38   71.38   71.38   71.37   71.37   71.37
   71.37   71.37   71.37   71.37   71.37   71.37   71.36   71.36   71.36   71.36
   71.36   71.37   71.38   71.43   71.59   71.59    71.6   71.59   71.58   71.56
    71.6   71.59   71.53   71.52    71.5    71.5   71.52   71.56    71.6    71.6
    71.6    71.6    71.6    71.6    71.6    71.6    71.6    71.6    71.6    71.6
   71.52   70.52   70.22   70.82   69.62   69.92   71.02   70.52   68.62   69.62
   69.22   69.82   68.62   69.42   68.72   70.72   68.82   69.92   68.22   69.62
   70.02   68.12   67.72   69.22   67.92   68.92   68.32   66.62   68.22   67.02
    68.8   68.31   66.59   67.45   67.61   67.61   66.66   69.05   68.15   68.64
   67.02   68.02   67.52   68.82   68.12   69.22   67.62   67.32   68.92   66.42
   68.12   67.02   67.12   67.52   68.92   67.22   68.52   69.72   71.12   71.52
Pier Skew, UpSta & Num, DnSta & Num=  ,4984.1, 2 ,4984.1, 2 , 0 , 0 , 0 ,,
     1.2     1.2
   58.11   68.59
     1.2     1.2
   58.03   68.51
Pier Skew, UpSta & Num, DnSta & Num=  ,5014.7, 2 ,5014.7, 2 , 0 , 0 , 0 ,,
     1.2     1.2
   55.84   68.63
     1.2     1.2
   55.76   68.55
Abutment Skew #Up #Dn= , 2 , 2
  4938.9  4940.5
   67.51   66.63
  4938.9  4940.5
   67.43   66.55
Abutment Skew #Up #Dn= , 2 , 2
  5058.5 5059.59
    66.7   67.69
  5058.5 5059.59
   66.62   67.61
BR Coef= 1 , 1 , 0 ,1.25, 0 ,,,.8,0,2,0,
WSPro=,,,, 1 ,,,, 0 ,,,, 0 ,,,,-1 ,-1 ,-1 , 0 , 0 , 0 , 0 , 0
BR U #Sta/Elev= 157
  3557.8    71.6  3568.3    70.6  3673.3    70.6  3698.3    70.3  3733.3    70.9
  3758.3    70.3  3893.3    70.3  3907.8   70.01  3908.3      70  3953.3    69.9
  3983.3    70.1  3993.3    69.7  4043.3      70  4058.3    71.1  4073.3    70.6
  4088.3    69.3  4093.3    68.7  4103.3    69.6  4108.3    69.7  4118.3    69.3
  4178.3    69.3  4198.3    69.9  4213.3    68.8  4218.3    68.7  4231.9      69
  4271.9    69.2  4321.9      69  4351.9    69.5  4376.9    68.8  4396.9    69.1
  4401.9    69.3  4411.9    70.2  4426.9    70.8  4431.9    70.7  4441.9    69.4
  4446.9    68.9  4471.9    69.2  4476.9    69.6  4491.9      70  4496.9    69.5
  4506.9    68.3  4511.9    68.5  4521.9    69.7  4536.9    70.1  4541.9    69.9
  4556.9    68.2  4586.9    67.8  4591.9    67.9  4601.9    68.6  4616.9    69.3
  4646.9      68  4661.9      68  4681.9      69  4696.9      69  4711.9    68.4
  4716.9    67.5  4726.9    66.7  4731.9      67  4741.9    68.3  4771.9    67.7
  4776.9    67.1    4783   68.88 4817.99   68.66  4818.1   68.66 4818.21   68.66
  4823.4   68.62    4824   68.62    4863   68.39  4920.4   67.14  4938.9   66.67
 4939.01   66.67  4939.1   66.67  4939.2   66.66  4940.4   66.63  4940.5   66.63
  4946.2   66.54  4969.6   66.17  4978.6   63.85  4984.1   58.53  4984.5   60.69
  4997.6   56.84  5003.7   56.89  5014.1   56.84  5014.7   57.69  5015.5   57.49
  5026.7   67.25  5051.2   67.49  5058.4   66.71  5058.5    66.7  5059.3   66.73
 5059.39   66.74  5059.5   66.74  5059.6   66.75  5114.7   69.13  5166.2   68.23
  5201.7   68.47  5242.6    68.7  5245.3   68.72  5245.4   68.72 5254.29   68.44
  5254.4   68.44 5254.51   68.44  5271.9    67.9  5277.4   67.72  5286.9    67.4
  5301.9    67.7  5311.9    67.2  5316.9    67.1  5331.9    67.7  5332.4   67.71
  5351.9    68.1  5366.9    67.8  5381.9    67.9  5386.9    67.6  5401.9      68
  5426.9    67.6  5431.9    67.8  5441.9    68.9  5461.9    68.5  5472.4   68.37
  5486.9    68.2  5491.9    68.3  5511.9    69.3  5521.9    68.9  5522.4   68.86
  5536.9    67.7  5551.9    67.7  5556.9    67.4  5582.4   67.54  5631.9    67.8
  5661.9    68.4  5736.9    68.7  5741.9      69  5801.9    67.2  5816.9    66.5
  5876.9    68.2  5891.9      68  5911.9    67.1  5957.4   66.83  5961.9    66.8
  6013.8    67.2  6023.8    67.7  6033.8    67.6  6043.8    68.8  6048.8      69
  6148.8    67.8  6158.8    67.8  6168.8    67.3  6178.8    67.4  6203.8    68.6
  6288.8    69.2  6313.8    69.9  6343.8    69.8  6358.8    70.1  6373.8    71.2
  6398.8    71.5  6467.4    71.6
BR U #Mann= 5
  3557.8      .2  3557.8      .1  4946.2     .14  4969.6    .045  5026.7     .14
BR U Banks=4969.6,5026.7
BR D #Sta/Elev= 157
  3557.8   71.52  3568.3   70.52  3673.3   70.52  3698.3   70.22  3733.3   70.82
  3758.3   70.22  3893.3   70.22  3907.8   69.93  3908.3   69.92  3953.3   69.82
  3983.3   70.02  3993.3   69.62  4043.3   69.92  4058.3   71.02  4073.3   70.52
  4088.3   69.22  4093.3   68.62  4103.3   69.52  4108.3   69.62  4118.3   69.22
  4178.3   69.22  4198.3   69.82  4213.3   68.72  4218.3   68.62  4231.9   68.92
  4271.9   69.12  4321.9   68.92  4351.9   69.42  4376.9   68.72  4396.9   69.02
  4401.9   69.22  4411.9   70.12  4426.9   70.72  4431.9   70.62  4441.9   69.32
  4446.9   68.82  4471.9   69.12  4476.9   69.52  4491.9   69.92  4496.9   69.42
  4506.9   68.22  4511.9   68.42  4521.9   69.62  4536.9   70.02  4541.9   69.82
  4556.9   68.12  4586.9   67.72  4591.9   67.82  4601.9   68.52  4616.9   69.22
  4646.9   67.92  4661.9   67.92  4681.9   68.92  4696.9   68.92  4711.9   68.32
  4716.9   67.42  4726.9   66.62  4731.9   66.92  4741.9   68.22  4771.9   67.62
  4776.9   67.02    4783    68.8 4817.99   68.58  4818.1   68.58 4818.21   68.58
  4823.4   68.54    4824   68.54    4863   68.31  4920.4   67.06  4938.9   66.59
 4939.01   66.59  4939.1   66.59  4939.2   66.58  4940.4   66.55  4940.5   66.55
  4946.2   66.46  4969.6   66.09  4978.6   63.77  4984.1   58.45  4984.5   60.61
  4997.6   56.76  5003.7   56.81  5014.1   56.76  5014.7   57.61  5015.5   57.41
  5026.7   67.17  5051.2   67.41  5058.4   66.63  5058.5   66.62  5059.3   66.65
 5059.39   66.66  5059.5   66.66  5059.6   66.67  5114.7   69.05  5166.2   68.15
  5201.7   68.39  5242.6   68.62  5245.3   68.64  5245.4   68.64 5254.29   68.36
  5254.4   68.36 5254.51   68.36  5271.9   67.82  5277.4   67.64  5286.9   67.32
  5301.9   67.62  5311.9   67.12  5316.9   67.02  5331.9   67.62  5332.4   67.63
  5351.9   68.02  5366.9   67.72  5381.9   67.82  5386.9   67.52  5401.9   67.92
  5426.9   67.52  5431.9   67.72  5441.9   68.82  5461.9   68.42  5472.4   68.29
  5486.9   68.12  5491.9   68.22  5511.9   69.22  5521.9   68.82  5522.4   68.78
  5536.9   67.62  5551.9   67.62  5556.9   67.32  5582.4   67.46  5631.9   67.72
  5661.9   68.32  5736.9   68.62  5741.9   68.92  5801.9   67.12  5816.9   66.42
  5876.9   68.12  5891.9   67.92  5911.9   67.02  5957.4   66.75  5961.9   66.72
  6013.8   67.12  6023.8   67.62  6033.8   67.52  6043.8   68.72  6048.8   68.92
  6148.8   67.72  6158.8   67.72  6168.8   67.22  6178.8   67.32  6203.8   68.52
  6288.8   69.12  6313.8   69.82  6343.8   69.72  6358.8   70.02  6373.8   71.12
  6398.8   71.42  6467.4   71.52
BR D #Mann= 5
  3557.8      .2  3557.8      .1  4946.2     .14  4969.6    .045  5026.7     .14
BR D Banks=4969.6,5026.7
BC Design=,, 0 ,, 0 ,,,,,,

Type RM Length L Ch R = 1 ,4834.0  ,379.6,379.6,379.6
BEGIN DESCRIPTION:
Downstream Section of Bridge/Culvert/Weir
END DESCRIPTION:
XS GIS Cut Line= 4
       3146161.7     13915576.19      3146002.16     13915014.83
      3145777.62     13914240.75      3145376.25     13912774.66
#Sta/Elev= 30
  3557.8   71.42  4058.3   70.92  4093.3   68.52  4376.9   68.62  4426.9   70.62
  4506.9   68.12  4536.9   69.92  4586.9   67.62  4696.9   68.82  4726.9   66.52
  4741.9   68.12  4776.9   66.92    4783    68.7  4946.2   66.36  4969.6   65.99
  4978.6   63.67  4984.1   58.35  4984.5   60.51  4997.6   56.66  5014.1   56.66
  5026.7   67.07  5114.7   68.95  5316.9   66.92  5511.9   69.12  5556.9   67.22
  5741.9   68.82  5816.9   66.32  6048.8   68.82  6168.8   67.12  6467.4   71.42
#Mann= 5 , 1 , 0
  3557.8      .2       0  3557.8      .1       0  4946.2     .14       0
  4969.6    .045       0  5026.7     .14       0
#XS Ineff= 2 , 0
       0    4928   71.37    5069       0   71.57
Permanent Ineff=
       F       F
Bank Sta=4969.6,5026.7
XS Rating Curve= 0
Exp/Cntr=.5,.3

Type RM Length L Ch R = 1 ,4454.4  ,572,544.6,513.3
BEGIN DESCRIPTION:
Cross Section  4454.4
END DESCRIPTION:
XS GIS Cut Line= 5
      3146291.19     13915026.06      3146084.37     13914145.61
      3146001.65     13913861.98       3145582.1     13912756.98
      3145310.29     13912626.98
#Sta/Elev= 30
  3964.6    71.1  4659.6    68.6  4699.6    67.8  4734.6    64.9  4764.6    65.1
  4789.6    67.2    4869      68  4915.2   67.05  4925.4   62.48  4938.7   59.26
  4985.8   58.12  4994.2   54.09  5000.2   53.02  5004.6   53.91  5008.4   58.03
  5024.8   60.78  5038.5    66.4  5062.1   66.03    5094    67.9    5154    67.1
  5199.5    69.1  5374.5    68.1  5519.5    68.9  5584.5    71.2  5619.5    68.2
  5794.5    67.4  6094.5    69.6  6214.5    68.3  6566.4    68.9  6647.7    70.8
#Mann= 5 , 1 , 0
  3964.6      .2       0  3964.6      .1       0  4915.2     .04       0
  5038.5     .14       0  6647.7      .2       0
#XS Ineff= 2 , 0
       0    4866   67.99               0
Permanent Ineff=
       F       F
Bank Sta=4915.2,5038.5
XS Rating Curve= 0
Exp/Cntr=.3,.1

Type RM Length L Ch R = 1 ,3909.8  ,715.4,615.3,556.9
BEGIN DESCRIPTION:
Cross Section  3909.8 - Interpolated
END DESCRIPTION:
XS GIS Cut Line= 6
      3146709.39     13915125.23      3146663.86     13914205.71
      3146572.82     13913887.06       3145862.7     13912985.75
      3145580.47     13912730.84      3145309.97     13912609.79
#Sta/Elev= 30
  3758.6    69.3  3868.6      67  3964.6   68.98  4138.6    67.9  4183.6    65.7
  4283.6    68.5  4469.6    65.6  4539.6      68  4639.6    67.6  4789.2    64.1
  4824.2      66  4956.4   66.39  4979.9    58.6    5027   57.46  5041.4   52.36
  5045.8   53.25  5049.6   57.37    5066   60.12  5079.7   65.74  5390.6    67.1
  5545.6    72.9  5616.5    67.9  5781.5    69.7  6116.5      68  6156.5    70.2
  6218.8    68.2  6403.8      70  6647.7   68.98  6794.1      69  6835.5    71.3
#Mann= 5 , 1 , 0
  3758.6      .2       0  3964.6      .1       0  4956.4     .04       0
  5079.7     .14       0  6647.7      .2       0
#XS Ineff= 2 , 0
       0    4916   66.65               0
Permanent Ineff=
       F       F
Bank Sta=4956.4,5079.7
XS Rating Curve= 0
Exp/Cntr=.3,.1

Type RM Length L Ch R = 1 ,3294.5  ,615.3,1006.2,1318
BEGIN DESCRIPTION:
Cross Section 3294.5
END DESCRIPTION:
XS GIS Cut Line= 6
        3147473.     13914801.52      3147378.46     13914033.34
      3147230.73     13913737.89       3146947.1     13913507.43
      3145759.38     13912774.71      3145292.56     13912585.62
#Sta/Elev= 30
  3767.7    67.4  4112.7    66.2  4197.7    63.8  4636.7    66.4  4791.7      64
    4882    67.1    4947    64.1  4958.6   65.37  4977.5   58.63  4989.3   56.85
  4991.3   53.52  4998.3   51.62  5003.5   52.56  5008.9   56.91  5029.5   55.31
    5067   58.31  5084.8   64.76    5107    63.5  5302.5      66  5852.3    66.5
  5962.3    68.8  6052.3    66.4  6212.3    66.5    6733    68.4    6758    69.8
    6918    68.7    7018    70.6    7053    68.8    7113    71.5  7136.7    70.1
#Mann= 5 , 1 , 0
  3767.7      .2       0  3767.7      .1       0  4958.6     .04       0
  5084.8     .14       0  7136.7      .2       0
#XS Ineff= 2 , 0
       0    4875    67.2               0
Permanent Ineff=
       F       F
Bank Sta=4958.6,5084.8
XS Rating Curve= 0
Exp/Cntr=.3,.1

Type RM Length L Ch R = 1 ,2288.3  ,548.7,593.7,540.4
BEGIN DESCRIPTION:
Cross Section 2288.3
END DESCRIPTION:
XS GIS Cut Line= 4
      3147592.64     13914792.43      3147880.73     13913495.62
      3147939.82     13913040.62      3148477.81     13911846.24
#Sta/Elev= 30
  3349.8      68  3709.8    66.5  3744.8    64.6  3819.8    66.8  4004.8    65.3
    4257   66.32  4768.2    67.3  4863.2      66  4888.2    64.2  4919.1    64.6
  4933.9   58.72  4948.5   55.42  4970.2   54.29  4993.4   54.96  4999.3   52.44
  5006.9   54.58  5022.1   56.67  5044.8   65.52  5058.3   64.41  5088.2    66.4
  5262.8   66.19    5377    64.5  5762.6   64.94    5887    64.9    5937    66.6
    6037    66.8    6157    66.6    6232    65.3    6297    66.7    6447    67.3
#Mann= 7 , 1 , 0
  3349.8      .2       0  3349.8      .1       0    4257     .12       0
  4919.1     .04       0  5044.8     .12       0  5262.8     .14       0
  5762.6      .1       0
#XS Ineff= 2 , 0
       0                    5089       0   66.45
Permanent Ineff=
       F       F
Bank Sta=4919.1,5044.8
XS Rating Curve= 0
Exp/Cntr=.3,.1

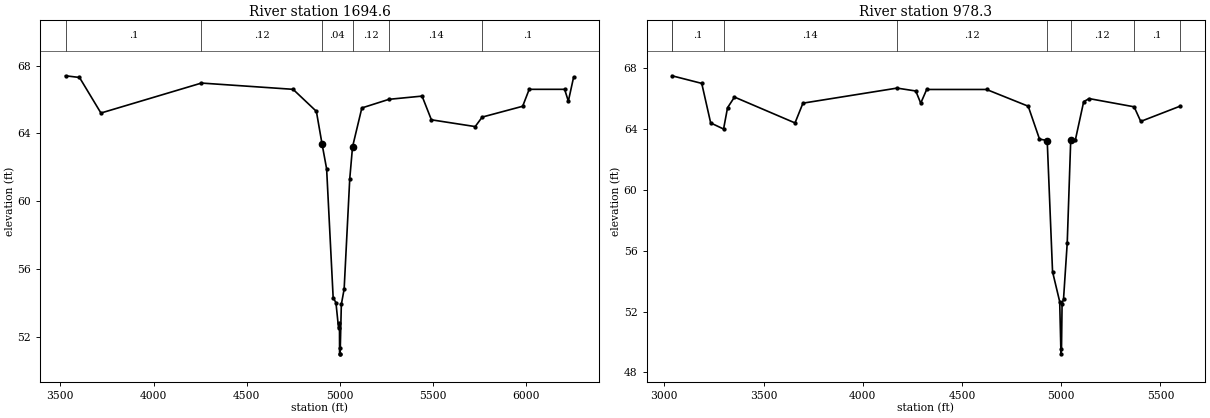
Type RM Length L Ch R = 1 ,1694.6  ,702.5,716.3,649.6
BEGIN DESCRIPTION:
Cross Section  1694.6 - Interpolated
END DESCRIPTION:
XS GIS Cut Line= 6
      3148029.49     13914706.44      3148319.91     13914046.93
       3148471.4      13913318.6      3148529.67     13912980.65
      3148675.34     13912555.31      3148909.79     13912150.41
#Sta/Elev= 30
  3527.7    67.4  3602.7    67.3  3717.7    65.2    4257   66.97  4748.3    66.6
  4873.3    65.3  4903.3    63.4  4928.3    61.9  4963.3    54.3  4978.3      54
  4992.2    52.5  4997.2    52.8  4997.8      51  4998.8   50.98  5001.5    51.3
  5007.2    53.9  5022.2    54.8  5052.2    61.3  5067.2    63.2  5117.2    65.5
  5262.8   66.01  5440.2    66.2  5490.2    64.8  5725.2    64.4  5762.6   64.96
  5979.8    65.6  6014.8    66.6  6204.8    66.6  6224.8    65.9  6252.7    67.3
#Mann= 6 , 1 , 0
  3527.7      .1       0    4257     .12       0  4903.3     .04       0
  5067.2     .12       0  5262.8     .14       0  5762.6      .1       0
Bank Sta=4903.3,5067.2
XS Rating Curve= 0
Exp/Cntr=.3,.1

Type RM Length L Ch R = 1 ,978.3   ,0,0,0
BEGIN DESCRIPTION:
Cross Section 978.3
END DESCRIPTION:
XS GIS Cut Line= 6
      3148081.64     13914706.97      3148808.45     13914222.43
      3149174.81     13913714.25      3149204.36     13913401.07
      3149157.09     13913117.44      3149292.99     13912680.17
#Sta/Elev= 30
  3038.7    67.5  3188.7      67  3233.7    64.4  3298.7      64  3318.7    65.4
  3353.7    66.1  3658.7    64.4  3698.7    65.7  4172.9   66.69  4267.2    66.5
  4292.2    65.7  4322.2    66.6  4623.7    66.6  4833.7    65.5  4890.6   63.34
  4929.5   63.24  4956.4   54.62  4992.4   52.65  4998.8   49.22  5001.5   49.54
  5004.4   52.48  5011.9   52.85  5030.4   56.52    5048   63.28    5071   63.26
  5113.3    65.8  5140.8      66  5367.4   65.46  5400.8    64.5  5598.7    65.5
#Mann= 8 , 1 , 0
  3038.7      .2       0  3038.7      .1       0  3298.7     .14       0
  4172.9     .12       0  4929.5     .04       0    5048     .12       0
  5367.4      .1       0  5598.7      .2       0
Bank Sta=4929.5,5048
XS Rating Curve= 0
Exp/Cntr=.3,.1

Chan Stop Cuts=-1